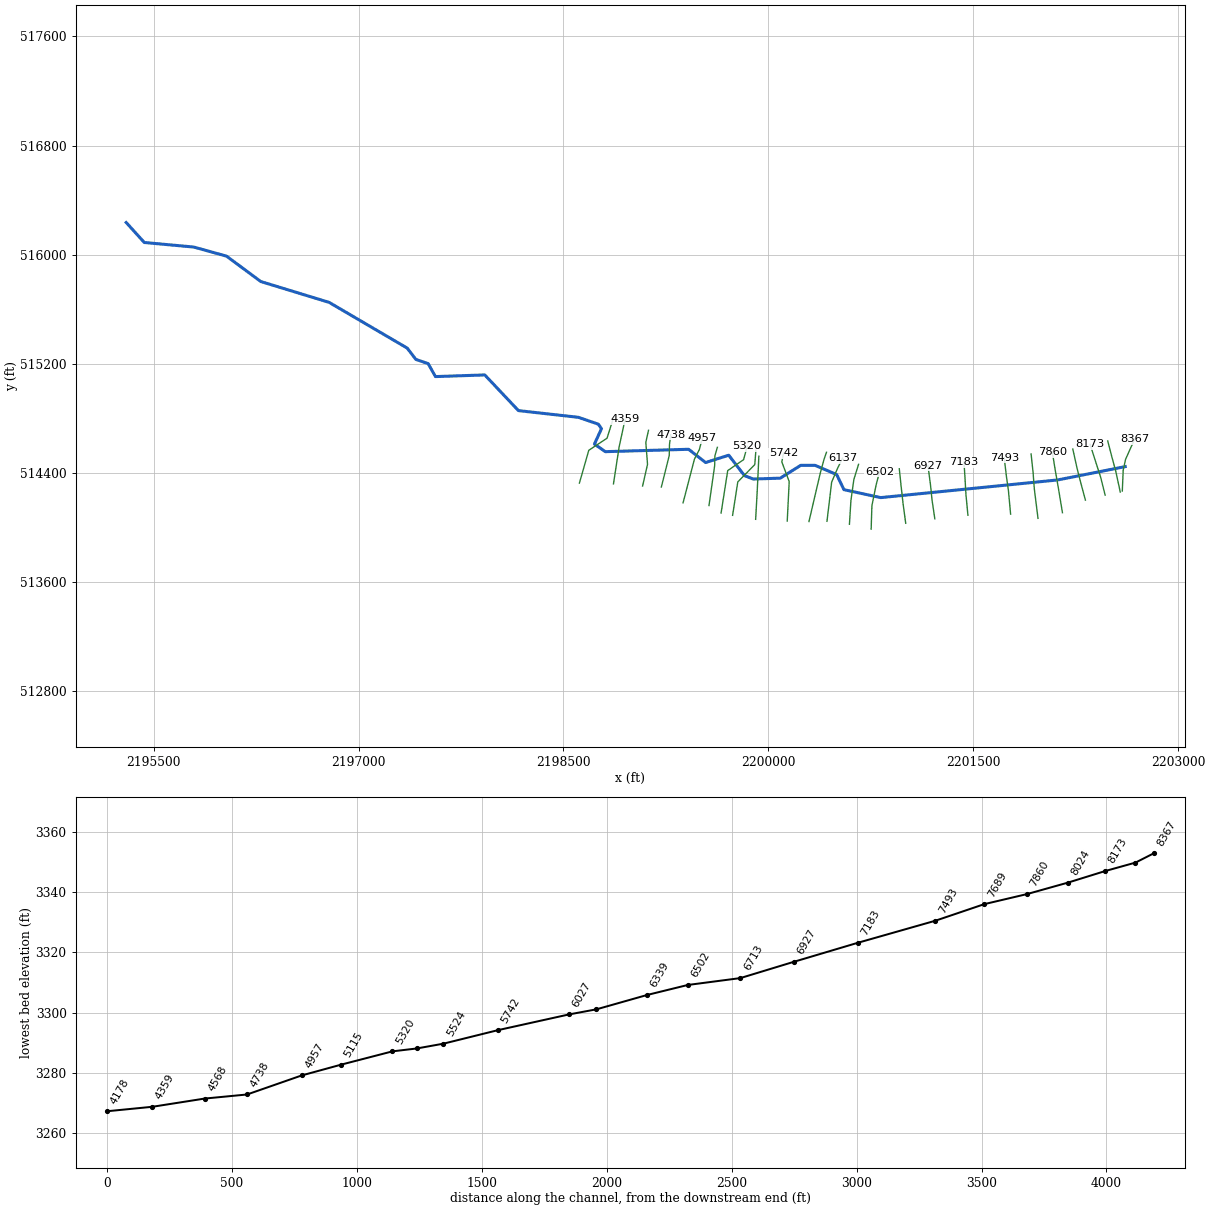
--- NFGAULYRV.prj (project) ---

Proj Title=NFGAULYRV
Current Plan=p01
Default Exp/Contr=0,0
English Units
Geom File=g01
Flow File=f01
Plan File=p01
Background Map Layer=Inundation Boundary (01pct Value_0)
Y Axis Title=Elevation
X Axis Title(PF)=Main Channel Distance
X Axis Title(XS)=Station
BEGIN DESCRIPTION:
----------MODEL BY WOOD PLC 2021----------
Stream Name: North Fork Gauley River
Flood Zone: Approximate
Pocahontas County, WV
HEC-RAS Version: RAS 6.1
Vertical Datum: NAVD88
Projection: NAD 1983 StatePlane West Virginia S FIPS 4702 (US Feet)
Terrain: 1-meter LIDAR (FEMA Region III 3DEP collected 2016-2018)
Land Use: 2019 NLCD
Hydrologic Method:
WV 2010 Regional Regression Equations
Model Notes:
Model extends beyond county boundary on the downstream end
END DESCRIPTION:
DSS Export Rating Curves= 0
DSS Export Rating Curve Sorted= 0
DSS Export Volume Flow Curves= 0
DXF OffsetX= 0
DXF OffsetY= 0
DXF ScaleX= 0
DXF ScaleY= 0

--- NFGAULYRV.p01 (plan) ---

Plan Title=Floodplain
Program Version=6.10
Short Identifier=Floodplain
Geom File=g01
Flow File=f01
Subcritical Flow
K Sum by GR= 0
Std Step Tol= 0.01
Critical Tol= 0.01
Num of Std Step Trials= 20
Max Error Tol= 0.3
Flow Tol Ratio= 0.001
Split Flow NTrial= 30
Split Flow Tol= 0.02
Split Flow Ratio= 0.02
Log Output Level= 0
Friction Slope Method= 1
Unsteady Friction Slope Method= 2
Unsteady Bridges Friction Slope Method= 1
Parabolic Critical Depth
Global Vel Dist= 0 , 0 , 0
Global Log Level= 0
CheckData=True
Encroach Param=-1 ,0,0, 0
Mapping Interval=1HOUR
Computation Time Step Use Courant=        0
Computation Time Step Use Time Series=    0
Computation Time Step Count To Double=0
Computation Time Step Max Doubling=0
Computation Time Step Max Halving=0
Computation Time Step Residence Courant=0
Run HTab= 0
Run UNet= 0
Run Sediment= 0
Run PostProcess= 0
Run WQNet= 0
Run RASMapper=-1
UNET Theta= 0
UNET Theta Warmup= 0
UNET ZTol= 0
UNET ZSATol= 0
UNET MxIter= 0
UNET Max Iter WO Improvement= 0
UNET MaxInSteps= 0
UNET DtIC= 0
UNET DtMin= 0
UNET MaxCRTS= 0
UNET WFStab= 0
UNET SFStab= 0
UNET WFX= 1
UNET SFX= 1
UNET Gravity=32.174
UNET 1D Methodology=Finite Difference
UNET DSS MLevel= 1
UNET Pardiso=0
UNET DZMax Abort= 0
UNET Use Existing IB Tables= 0
UNET Froude Reduction=False
UNET Froude Limit= 0
UNET Froude Power= 0
UNET D1 Cores= 0
UNET WindReference=Eulerian
UNET WindDragFormulation=Hsu (1988)
UNET D2 Coriolis=0
UNET D2 Cores= 0
UNET D2 Theta= 1
UNET D2 Theta Warmup= 1
UNET D2 Z Tol= 0.01
UNET D2 Volume Tol= 0.01
UNET D2 Max Iterations= 20
UNET D2 Equation= 0
UNET D2 RampUpFraction=0.1
UNET D2 TimeSlices= 1
UNET D2 Turbulence Formulation=Non-Conservative (original)
UNET D2 Eddy Viscosity=0.3
UNET D2 Transverse Eddy Viscosity=0.1
UNET D2 Smagorinsky Mixing=0
UNET D2 BCVolumeCheck=0
UNET D2 Cores=0
UNET D2 SolverType=PARDISO (Direct)
UNET D2 Minimum Iterations= 2147483647
UNET D2 Maximum Iterations= 2147483647
UNET D2 Restart Number= 10
UNET D2 Relaxation Coeff=1.3
UNET D2 SOR Precondition Iterations= 10
UNET D2 ILUT Maximum Fill= 8
UNET D2 ILUT Tolerance=1E-08
UNET D1D2 MaxIter= 0
UNET D1D2 ZTol=0.01
UNET D1D2 QTol=0.1
UNET D1D2 MinQTol=1
Write IC File= 0
Write IC File at Fixed DateTime=0
Write IC File at Sim End=0
Echo Input=False
Echo Parameters=False
Echo Output=False
Write Detailed= 0
HDF Write Warmup=0
HDF Write Time Slices=0
HDF Flush=0
HDF Compression= 1
HDF Chunk Size= 1
HDF Spatial Parts= 1
HDF Use Max Rows=0
HDF Fixed Rows= 1
Calibration Method= 0
Calibration Iterations= 20
Calibration Max Change=0.05
Calibration Tolerance=0.2
Calibration Maximum=1.5
Calibration Minimum=0.5
Calibration Optimization Method= 1
WQ AD Non Conservative
WQ ULTIMATE=-1
WQ Max Comp Step=1HOUR
WQ Output Interval=15MIN
WQ Output Selected Increments= 0
WQ Output face flow=0
WQ Output face velocity=0
WQ Output face area=0
WQ Output face dispersion=0
WQ Output cell volume=0
WQ Output cell surface area=0
WQ Output cell continuity=0
WQ Output cumulative cell continuity=0
WQ Output face conc=0
WQ Output face dconc_dx=0
WQ Output face courant=0
WQ Output face peclet=0
WQ Output face adv mass=0
WQ Output face disp mass=0
WQ Output cell mass=0
WQ Output cell source sink temp=0
WQ Output nsm pathways=0
WQ Output nsm derived pathways=0
WQ Create Restart=0
WQ Fixed Restart=0
WQ System Summary=0
WQ Write To DSS=0
Sorting and Armoring Iterations= 10
XS Update Threshold= 0.02
Bed Roughness Predictor= 0
Hydraulics Update Threshold= 0.02
Energy Slope Method= 1
Volume Change Method= 1
Sediment Retention Method= 0
Sediment TS Multiplier= 1
Warm Up Method= 0
XS Weighting Method= 0
Number of US Weighted Cross Sections= 1
Number of DS Weighted Cross Sections= 1
Upstream XS Weight=0
Main XS Weight=1
Downstream XS Weight=0
Number of DS XS's Weighted with US Boundary= 1
Upstream Boundary Weight= 1
Weight of XSs Associated with US Boundary= 0
Number of US XS's Weighted with DS Boundary= 1
Downstream Boundary Weight= 0.5
Weight of XSs Associated with DS Boundary= 0.5
Percentile Method= 0
Sediment Output Level= 3
Mass or Volume Output= 0
Output Increment Type= 1
Profile and TS Output Increment= 1
Transport Output Increment 1
XS Output Flag= 0
XS Output Increment= 10
Read HDF5 Sediment Hotstart= 0
Sediment Hotstart Type= 0
Write Gradation File= 0
Read Gradation Hotstart= 0
Write HDF5 File= 1
Write Binary Output= 1
Write DSS Sediment File= 0
DSS Sediment Output Type= 1
SV Curve= 0
Specific Gage Flag= 0
Subcell Erosion Methods= 0
Subcell Deposition Methods= 0
Advection Scheme= 1
Matrix Solver= 0
Implicit Weighting Factor= 1
Maximum Outer Loop Convergence Iterations= 5
Convergence Maximum Absolute= 0.001
Convergence RMSE= 0.0001
Grain Fractions Max Abs Error= 0.001
Max Subgrid Regions= 1
Max Subgrid Length Scale= 3.402823E+38
Initial Layer Thickness= 3.402823E+38
Min Layer Thickness= 3.402823E+38
Max Layer Thickness= 3.402823E+38
Number of Layers= 5

--- NFGAULYRV.f01 (steady flow) ---

Flow Title=Flow
Program Version=6.10
Number of Profiles= 6
Profile Names=01pct,10pct,04pct,02pct,0_2pct,01plus
River Rch & RM=NFGAULYRV,Main            ,8367
     717     382     506     609     998    1060
River Rch & RM=NFGAULYRV,Main            ,4957
     803     430     568     682    1110    1190
River Rch & RM=NFGAULYRV,Main            ,1716
    1060     572     752     900    1460    1560
River Rch & RM=NFGAULYRV,Main            ,1244
    1220     662     868    1037    1676    1800
Boundary for River Rch & Prof#=NFGAULYRV,Main            , 1
Up Type= 0
Dn Type= 1
Dn Known WS=3176.3
Boundary for River Rch & Prof#=NFGAULYRV,Main            , 2
Up Type= 0
Dn Type= 1
Dn Known WS=3175.4
Boundary for River Rch & Prof#=NFGAULYRV,Main            , 3
Up Type= 0
Dn Type= 1
Dn Known WS=3175.8
Boundary for River Rch & Prof#=NFGAULYRV,Main            , 4
Up Type= 0
Dn Type= 1
Dn Known WS=3176.1
Boundary for River Rch & Prof#=NFGAULYRV,Main            , 5
Up Type= 0
Dn Type= 1
Dn Known WS=3177.1
Boundary for River Rch & Prof#=NFGAULYRV,Main            , 6
Up Type= 0
Dn Type= 1
Dn Known WS=3177.3
DSS Import GetInterval= 0
DSS Import GetPeak= 0
DSS Import FillOption= 0

--- NFGAULYRV.g01 (geometry) ---

Geom Title=Geometry
Program Version=6.10

River Reach=NFGAULYRV       ,Main
Reach XY= 30
     2202612.583      514447.554     2202116.887      514349.536
     2200822.272      514220.426      2200553.09      514278.566
     2200500.203      514389.368     2200342.797      514456.507
     2200236.804        514456.8     2200087.266      514362.854
     2199889.531      514356.392     2199824.764      514381.661
     2199710.069      514531.062     2199540.569      514477.382
     2199416.403       514574.45     2198806.534      514557.057
     2198726.688      514612.564     2198778.587      514725.111
     2198755.431      514758.401     2198608.813      514808.823
     2198170.437      514857.877     2197924.164       515119.22
     2197563.073       515107.12     2197509.704      515202.254
     2197419.683      515232.834      2197356.08      515315.999
     2196784.808      515650.783     2196284.556      515803.594
     2196033.504      515989.637     2195793.879      516056.283
     2195431.574      516089.669     2195299.202      516236.131

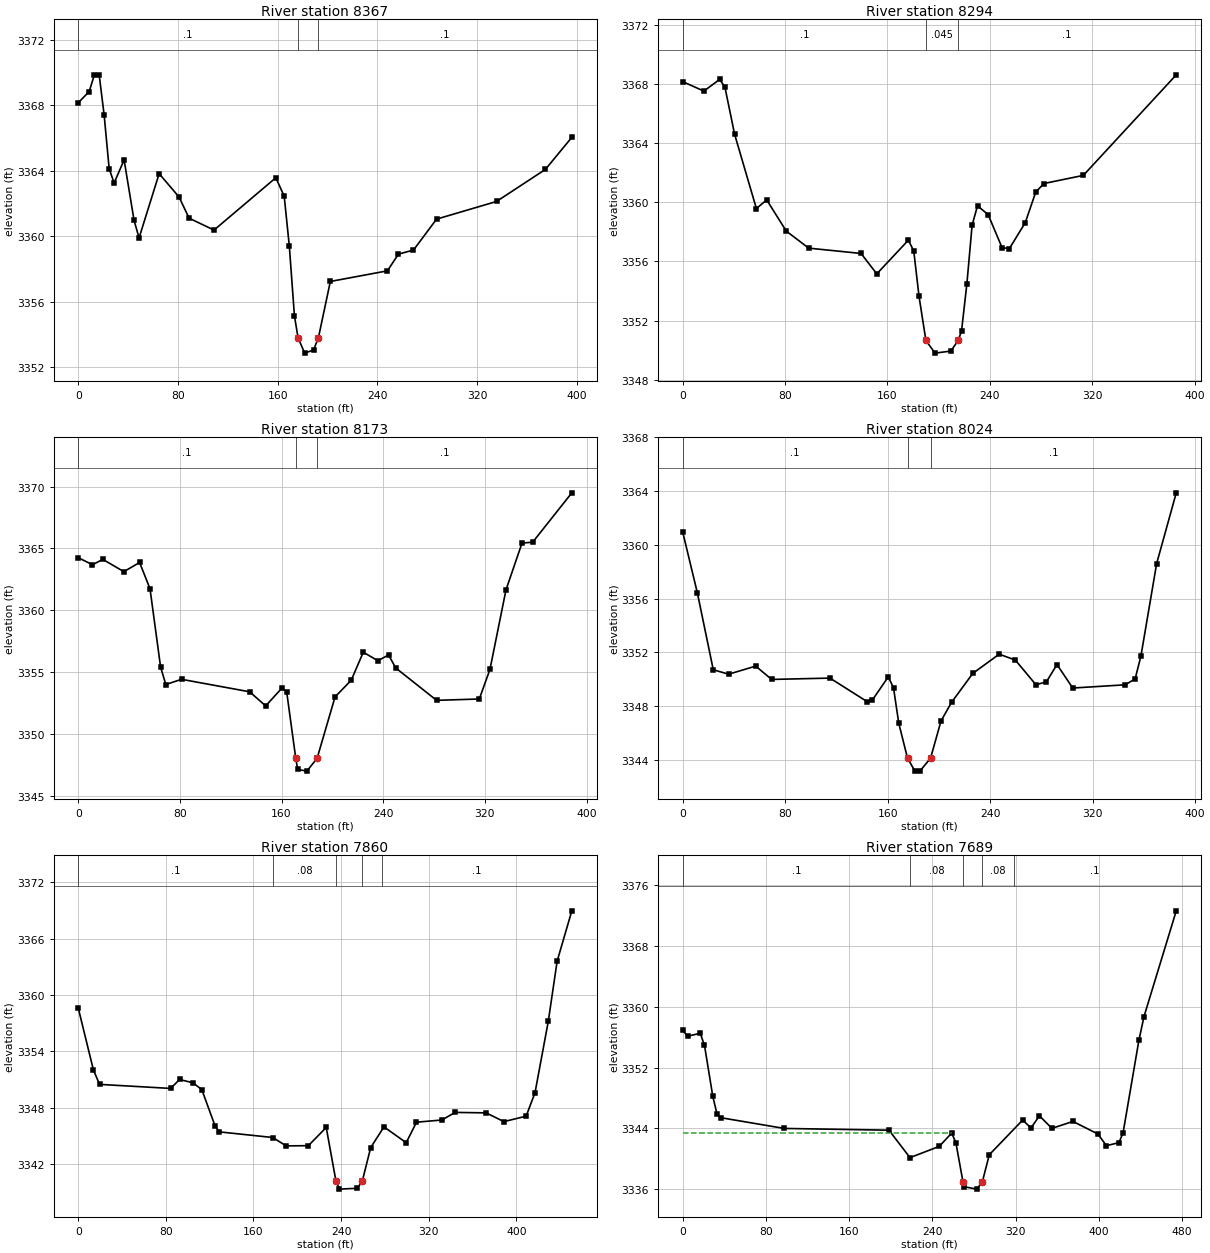
Type RM Length L Ch R = 1 ,8367    ,66.3,72.4,81.8
XS GIS Cut Line= 4
2202591.16018061514268.3852773832202597.56196266 514420.96108289
2202614.63338145514499.916394831 2202680.7851293514648.224345638
#Sta/Elev= 30
       0 3368.15     8.8 3368.84    12.8 3369.82    16.8 3369.86    20.8  3367.4
    24.8 3364.13    28.8 3363.25    36.8 3364.66    44.8 3360.96    48.8 3359.89
    64.9 3363.82    80.9 3362.39    88.9  3361.1   108.9 3360.37   158.5 3363.57
   165.2 3362.44   169.3  3359.4   173.4 3355.13   176.33353.793   181.6 3352.85
   188.7 3353.04  192.643353.791   202.2 3357.23     248 3357.88   256.8  3358.9
   268.9 3359.15   287.4 3361.04   335.5 3362.12   374.7 3364.08395.8823 3366.04
#Mann= 3 ,-1,0
       0      .1       0   176.3    .045       0  192.64      .1       0
Bank Sta=176.3,192.64
XS Rating Curve= 0 ,0
Exp/Cntr(USF)=0,0
Exp/Cntr=0.3,0.1

Type RM Length L Ch R = 1 ,8294    ,120.5,121.2,122.9
XS GIS Cut Line= 4
2202576.22268916514260.9165316592202542.07985156 514418.82715554
2202515.40575969514515.9208499542202484.46381312 514635.42078154
#Sta/Elev= 30
       0 3368.16    16.6 3367.52    28.9 3368.31      33  3367.8    40.6  3364.6
    57.6 3359.58    65.7 3360.16      81 3358.05    98.5  3356.9   139.4 3356.54
   151.7 3355.16   176.4 3357.44   180.6  3356.7   184.7 3353.64  190.07 3350.66
   197.2  3349.8   209.6 3349.94  215.28 3350.66   217.9 3351.28   222.1 3354.49
   226.2 3358.46   230.4 3359.76   238.7 3359.17   249.6 3356.93   255.3 3356.87
   267.7 3358.62   275.9 3360.69   282.3 3361.27   313.1 3361.82   385.7 3368.62
#Mann= 3 ,-1,0
       0      .1       0  190.07    .045       0  215.28      .1       0
Bank Sta=190.07,215.28
XS Rating Curve= 0 ,0
Exp/Cntr(USF)=0,0
Exp/Cntr=0.3,0.1

Type RM Length L Ch R = 1 ,8173    ,149.5,149.1,147.9
XS GIS Cut Line= 4
2202465.53288275514238.3244174132202433.00846041514368.422106774
2202396.87021337514480.4506726132202355.31122926514610.548361974
#Sta/Elev= 30
       0 3364.25    11.2 3363.68    19.4 3364.11    35.9 3363.12    48.3 3363.86
    56.5 3361.73    64.8 3355.42    68.9    3354    81.3 3354.42   134.9 3353.41
   147.5 3352.27   160.1 3353.69     164 3353.43  171.173348.034   172.7 3347.14
   179.9    3347  187.963348.034   202.1    3353   214.8 3354.34   224.3 3356.61
   235.8 3355.92   244.2 3356.39   249.8 3355.34     282 3352.72   315.6 3352.83
     324 3355.23   336.6 3361.65   349.2 3365.43   357.6  3365.5   388.4 3369.49
#Mann= 3 ,-1,0
       0      .1       0  171.17    .045       0  187.96      .1       0
Bank Sta=171.17,187.96
XS Rating Curve= 0 ,0
Exp/Cntr(USF)=0,0
Exp/Cntr=0.3,0.1

Type RM Length L Ch R = 1 ,8024    ,165.2,164.1,163.2
XS GIS Cut Line= 4
2202320.97989457514202.0746325692202286.64855988514330.365409578
 2202259.5448746 514436.973238362202228.82736461514576.105489482
#Sta/Elev= 30
       0 3360.96    11.5 3356.41    23.9  3350.7    35.9 3350.37      57 3350.97
    69.5 3349.98     115 3350.08     144 3348.33   148.1 3348.45   160.5 3350.17
   164.6 3349.36   168.7 3346.72  175.523344.125   181.1  3343.2   185.2 3343.16
  193.523344.127   201.7  3346.9     210 3348.29   226.5 3350.43   247.1 3351.86
   259.7 3351.42   275.8 3349.58     284 3349.81   292.2 3351.09   304.5 3349.34
   345.4 3349.58   353.2 3350.02   357.7 3351.71     370  3358.6   385.3 3363.86
#Mann= 3 ,-1,0
       0      .1       0  175.52    .045       0  193.52      .1       0
Bank Sta=175.52,193.52
XS Rating Curve= 0 ,0
Exp/Cntr(USF)=0,0
Exp/Cntr=0.3,0.1

Type RM Length L Ch R = 1 ,7860    ,172.1,171,168.5
XS GIS Cut Line= 4
2202152.93704581514109.9221026052202124.02644818514285.192600772
2202098.72967525514429.7455889512202078.85363937514554.422541255
#Sta/Elev= 30
       0 3358.62    13.9 3352.01    19.5 3350.49    84.4 3350.06    92.5 3351.01
   104.7 3350.66   112.8 3349.94   124.9 3346.08   128.8 3345.44   177.6 3344.84
   189.8 3343.95   210.1 3343.97   226.4 3345.91  235.243340.234   238.5 3339.35
   254.8 3339.44  259.393340.235     267 3343.77   279.1 3345.97   299.4 3344.29
   308.8 3346.47   331.9  3346.7   344.1 3347.51   372.4 3347.46   388.6 3346.53
   408.9 3347.11     417 3349.61   429.1 3357.19   437.2  3363.6   450.6 3368.95
#Mann= 5 ,-1,0
       0      .1       0  177.64     .08       0  235.24    .045       0
  259.39     .08       0  277.64      .1       0
Bank Sta=235.24,259.39
XS Rating Curve= 0 ,0
Exp/Cntr(USF)=0,0
Exp/Cntr=0.3,0.1

Type RM Length L Ch R = 1 ,7689    ,194.8,195.7,196.9
XS GIS Cut Line= 4
2201974.05272294514068.3631185032201946.94903766514285.192600772
 2201937.9144759 514404.448816022201923.45917708514539.967242437
#Sta/Elev= 30
       0 3356.88     4.9 3356.12    16.9  3356.5      21  3354.9      29 3348.19
    33.1 3345.84    37.1 3345.39    97.6 3343.99   198.3 3343.76   218.5 3340.15
   246.6 3341.63   258.6 3343.38   262.6 3342.11  269.383337.004   270.7 3336.32
   282.7 3336.01  288.113337.007   294.7 3340.53   326.8 3345.09   334.8 3344.05
   342.9 3345.65   354.9    3344   375.1 3344.91   399.2 3343.25   407.2 3341.72
   419.3 3342.12   423.3 3343.42   438.5 3355.58   443.4  3358.7   474.4  3372.6
#Mann= 5 ,-1,0
       0      .1       0  218.52     .08       0  269.38    .045       0
  288.11     .08       0  318.52      .1       0
#XS Ineff= 2 , 0
          258.53 3343.42
Permanent Ineff=
       T       F
Bank Sta=269.38,288.11
XS Rating Curve= 0 ,0
Exp/Cntr(USF)=0,0
Exp/Cntr=0.3,0.1

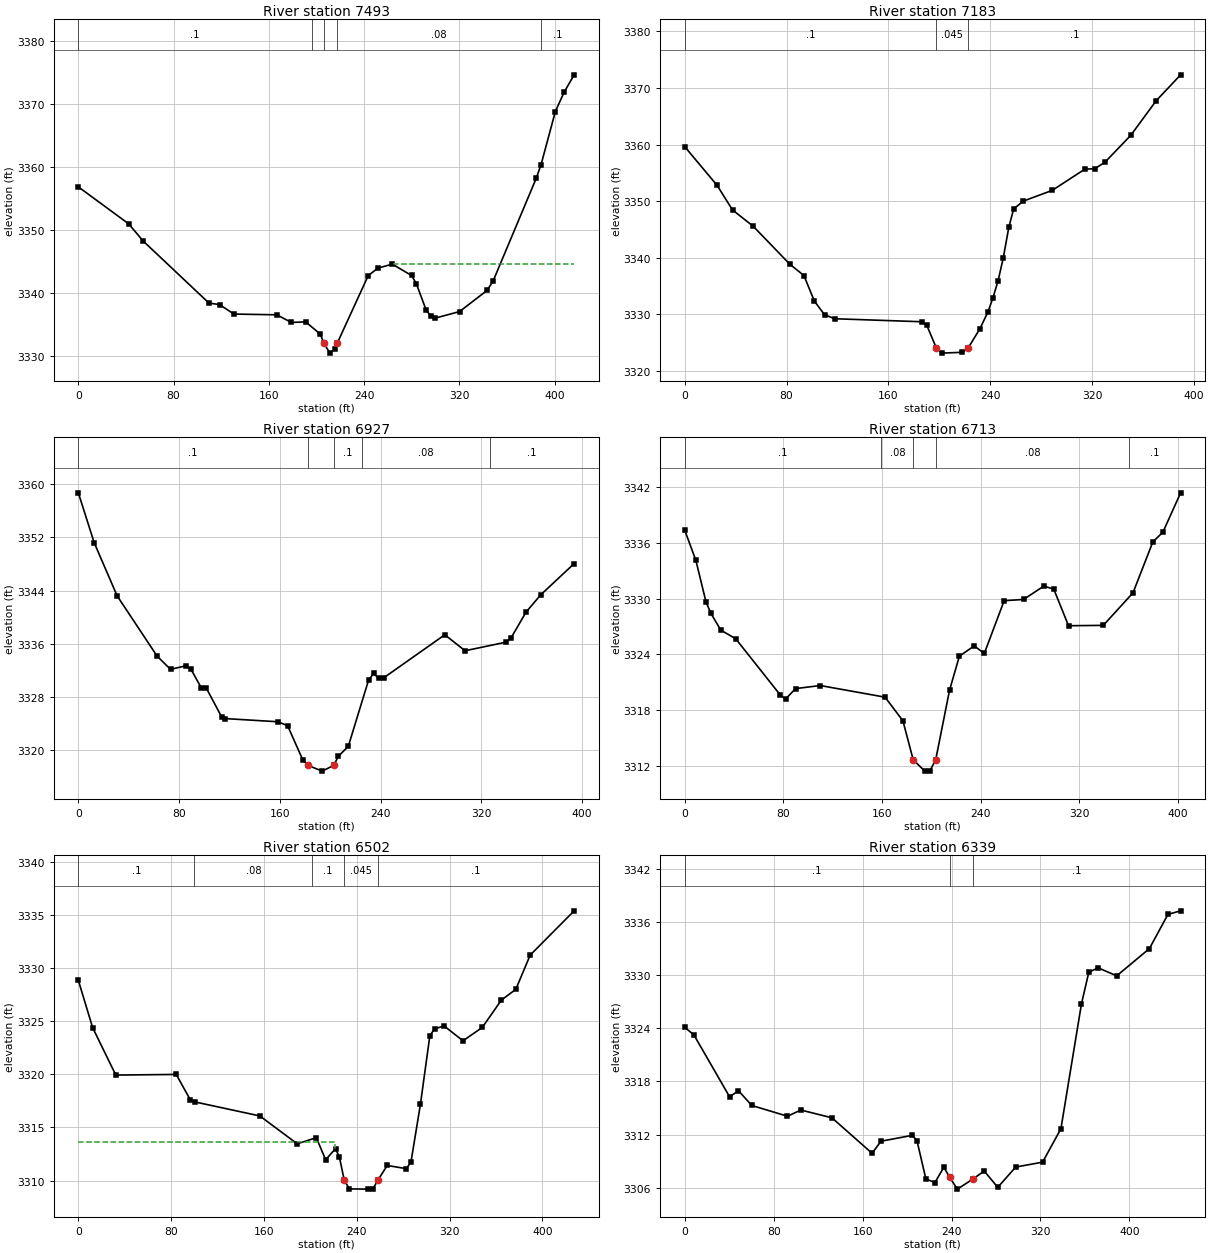
Type RM Length L Ch R = 1 ,7493    ,311.6,310.8,310.1
XS GIS Cut Line= 4
2201773.48545184514099.0806284912201757.22324067514274.351126659
2201742.76794186514375.5382183842201726.50573069514512.863557154
#Sta/Elev= 30
       0 3356.85    42.3 3350.99    54.3  3348.3   109.7 3338.44   118.6  3338.2
   130.7  3336.7   166.8 3336.58   178.9 3335.37     191 3335.46   203.1 3333.54
  206.473332.068   211.2 3330.51   215.2 3331.15  217.453332.066   243.5 3342.79
   251.6 3343.97   263.7 3344.61   279.9 3342.81   283.9 3341.53     292 3337.42
     296 3336.36     300 3336.07   320.2 3337.09   343.3 3340.44   348.4 3341.93
   384.6 3358.19   388.6 3360.31   400.7 3368.78   408.1 3371.86   416.5  3374.6
#Mann= 5 ,-1,0
       0      .1       0  196.02     .08       0  206.47    .045       0
  217.45     .08       0  388.24      .1       0
#XS Ineff= 2 , 0
                          264.03          3344.7
Permanent Ineff=
       F       F
Bank Sta=206.47,217.45
XS Rating Curve= 0 ,0
Exp/Cntr(USF)=0,0
Exp/Cntr=0.3,0.1

Type RM Length L Ch R = 1 ,7183    ,254.3,255.2,256.3
XS GIS Cut Line= 4
2201460.88961491514091.8529790832201446.43431609 514243.63361667
2201439.20666668514370.1174813272201431.97901727514480.339134814
#Sta/Elev= 30
       0 3359.61    25.4 3352.79    37.5 3348.45    53.6 3345.61    82.6 3338.86
    93.6 3336.88   101.8 3332.37   109.8 3329.95   117.9 3329.25   186.1 3328.72
   190.1 3328.12  197.733324.039   202.1 3323.18   218.1 3323.33  222.523324.039
   231.9 3327.49   238.2 3330.45   242.2 3332.99   246.2 3335.99   250.2 3339.94
   254.6 3345.39   258.4 3348.64     266 3350.02   288.7 3351.91   314.3 3355.65
   322.1 3355.74     330 3356.85   350.4 3361.62   370.4 3367.74   389.6 3372.31
#Mann= 3 ,-1,0
       0      .1       0  197.73    .045       0  222.52      .1       0
Bank Sta=197.73,222.52
XS Rating Curve= 0 ,0
Exp/Cntr(USF)=0,0
Exp/Cntr=0.3,0.1

Type RM Length L Ch R = 1 ,6927    ,214.5,214.8,214.7
XS GIS Cut Line= 4
2201218.76335971514064.7492937992201198.88732383514198.460807865
2201186.23893737514319.5239354642201168.16981384514455.042361882
#Sta/Elev= 30
       0 3358.71    12.6 3351.21    30.8 3343.23    62.5 3334.18    73.2 3332.18
    85.4 3332.72    89.4  3332.2    97.5 3329.44   101.5  3329.4   113.7 3325.06
   116.2 3324.79   158.3 3324.31   166.1 3323.73   178.1 3318.61  182.123317.767
   193.6 3316.89  202.883317.768   206.3  3319.1   214.3 3320.61   230.4 3330.57
   234.4 3331.58   238.4 3330.84   242.5 3330.92   290.9 3337.38     307 3334.98
   339.3 3336.26   343.3 3336.84   355.4 3340.78     367 3343.37   393.6 3348.08
#Mann= 5 ,-1,0
       0      .1       0  182.12    .045       0  202.88      .1       0
  225.18     .08       0   326.9      .1       0
Bank Sta=182.12,202.88
XS Rating Curve= 0 ,0
Exp/Cntr(USF)=0,0
Exp/Cntr=0.3,0.1

Type RM Length L Ch R = 1 ,6713    ,216.5,210.2,205.8
XS GIS Cut Line= 4
2201005.54770214514032.2248714592200985.67166627514180.391684342
2200971.21636745514310.4893737032200958.56798099514431.552501303
#Sta/Elev= 30
       0 3337.32       9 3334.09    17.1 3329.68    21.1 3328.42    29.2 3326.61
    41.3 3325.68    77.6 3319.62    81.7  3319.2    89.8 3320.33   109.9 3320.66
   162.4 3319.41   176.9 3316.87  185.213312.693   194.6 3311.47   198.7 3311.48
  203.483312.693   214.7 3320.16   222.7 3323.82   234.7 3324.91   242.9 3324.11
     259 3329.77   274.7  3329.9   291.1 3331.33   299.2 3331.02   311.2 3327.08
   339.4 3327.12   363.5 3330.62   379.6 3336.09   387.7 3337.12   402.1 3341.35
#Mann= 5 ,-1,0
       0      .1       0  159.49     .08       0  185.21    .045       0
  203.48     .08       0  360.39      .1       0
Bank Sta=185.21,203.48
XS Rating Curve= 0 ,0
Exp/Cntr(USF)=0,0
Exp/Cntr=0.3,0.1

Type RM Length L Ch R = 1 ,6502    ,162.9,163.3,164.3
XS GIS Cut Line= 4
2200752.57997283513988.8589750052200758.00070989514160.515648468
2200788.71821988514312.2962860562200814.01499281514409.869553076
#Sta/Elev= 30
       0 3328.87    12.3 3324.42    32.3 3319.94    84.4    3320    96.4 3317.63
   100.4 3317.41   156.4 3316.09   188.7 3313.46   205.1 3314.04   213.2 3311.96
   221.7 3313.01   225.1 3312.18  229.113310.087   233.6 3309.21     250 3309.19
     254 3309.22  258.513310.088   266.3 3311.42   282.6 3311.12   286.7 3311.72
   294.9  3317.2     303 3323.65   307.1  3324.3   315.3 3324.57   331.6 3323.17
   348.2 3324.43   364.7 3327.01   377.1 3328.02   389.5 3331.25   427.4 3335.42
#Mann= 5 ,-1,0
       0      .1       0     100     .08       0  201.74      .1       0
  229.11    .045       0  258.51      .1       0
#XS Ineff= 2 , 0
          221.12 3313.64
Permanent Ineff=
       F       F
Bank Sta=229.11,258.51
XS Rating Curve= 0 ,0
Exp/Cntr(USF)=0,0
Exp/Cntr=0.3,0.1

Type RM Length L Ch R = 1 ,6339    ,205.5,202.3,196.9
XS GIS Cut Line= 4
2200593.57168583 514024.997222052200604.41315995514198.460807865
2200626.09610817514353.8552701572200660.42744287514464.076923643
#Sta/Elev= 30
       0  3324.1     8.2 3323.25    40.3 3316.27    48.3 3316.95    60.3 3315.29
    92.4 3314.08   104.4 3314.78   132.4  3313.9   168.5  3309.9   176.5 3311.26
   204.8 3311.93   208.9 3311.32   216.9 3307.01     225  3306.6   233.1 3308.33
   238.3  3307.2   245.2 3305.86   258.9 3306.97   269.4  3307.9   281.6 3306.06
   297.7 3308.35   321.9  3308.9   338.4 3312.67   356.9 3326.76   363.5 3330.32
   371.9 3330.81   388.6 3329.91     418 3332.98   434.7 3336.84   446.1 3337.24
#Mann= 3 ,-1,0
       0      .1       0   238.3    .045       0   258.9      .1       0
Bank Sta=238.3,258.9
XS Rating Curve= 0 ,0
Exp/Cntr(USF)=0,0
Exp/Cntr=0.3,0.1

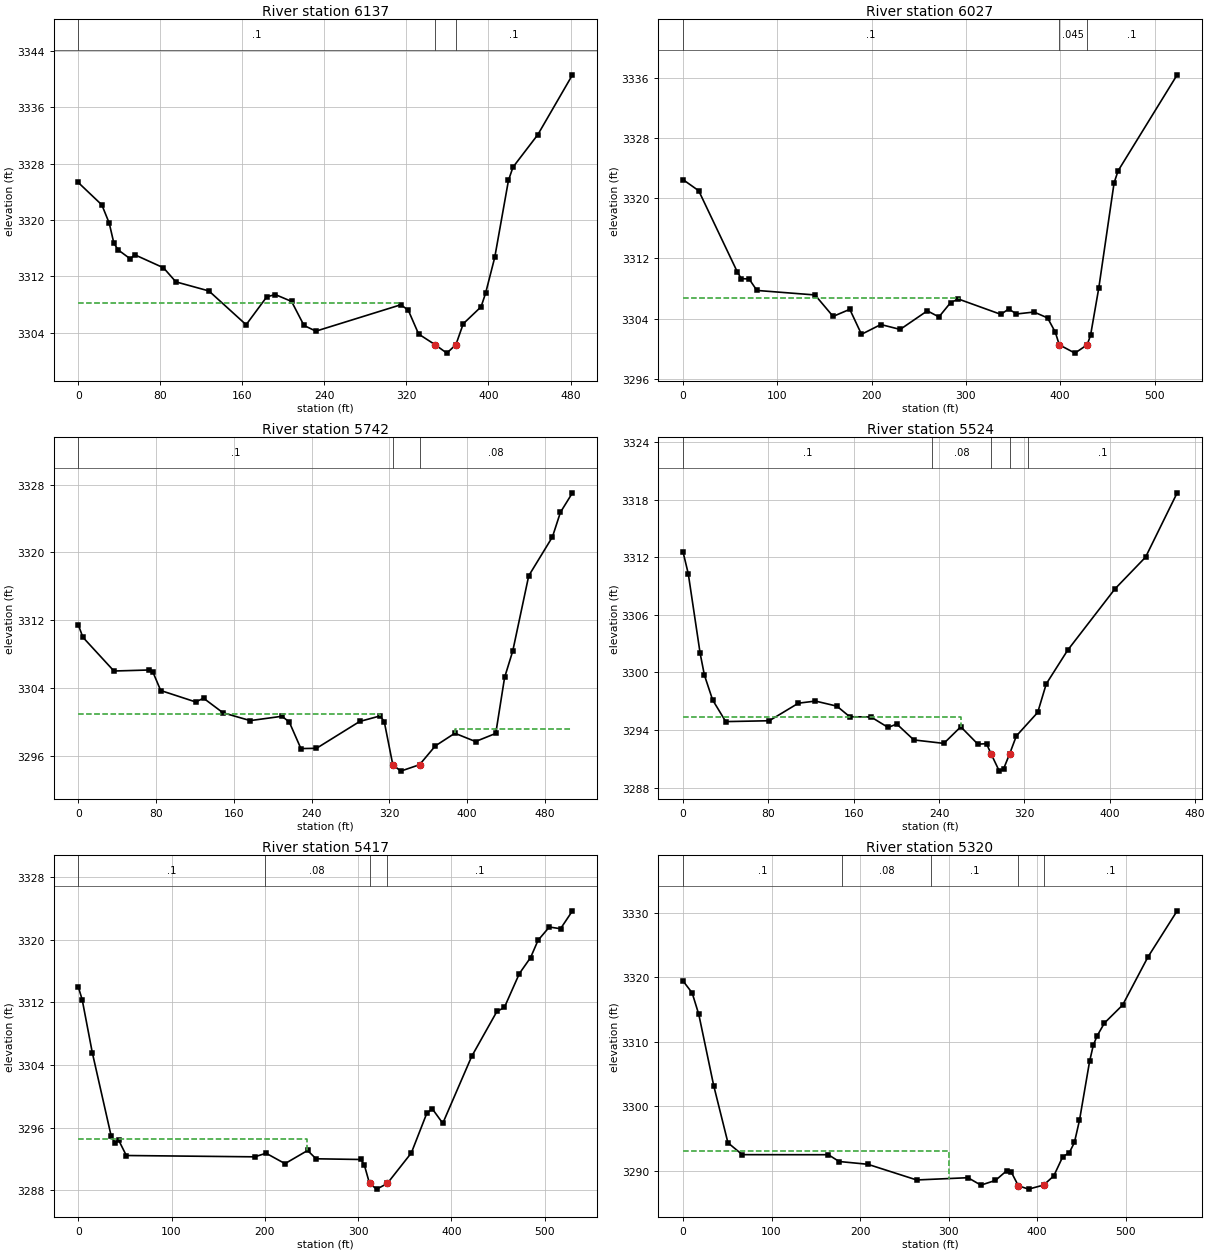
Type RM Length L Ch R = 1 ,6137    ,107.4,110.2,113.6
XS GIS Cut Line= 4
2200429.14266178514046.6801702772200463.47399647514333.979234282
2200505.03298057514431.5525013032200542.97813997514509.249732449
#Sta/Elev= 30
       0 3325.34      23 3322.16    30.2 3319.57    34.7 3316.74    38.8 3315.78
    50.9 3314.48    54.9 3315.09    83.1 3313.23    95.2 3311.23   127.4 3309.94
   163.7 3305.14   183.8  3309.1   192.1 3309.43     208 3308.45   220.1 3305.04
   231.7 3304.23   314.6 3307.98   321.8  3307.2   331.9 3303.82   347.93302.313
   359.4 3301.11  368.243302.313   375.4 3305.28   392.8 3307.69   397.2 3309.63
   406.1  3314.7   419.5 3325.65   423.9 3327.52   448.1 3332.13   481.9 3340.63
#Mann= 3 ,-1,0
       0      .1       0   347.9    .045       0  368.24      .1       0
#XS Ineff= 2 , 0
          314.08 3308.18
Permanent Ineff=
       F       F
Bank Sta=347.9,368.24
XS Rating Curve= 0 ,0
Exp/Cntr(USF)=0,0
Exp/Cntr=0.3,0.1

Type RM Length L Ch R = 1 ,6027    ,273.5,284.5,297.5
XS GIS Cut Line= 4
2200297.23806007514044.8732579242200380.35602827514400.834991315
2200407.45971355514500.2151706882200425.52883708514552.615628903
#Sta/Elev= 30
       0 3322.47    16.7 3320.99    57.8 3310.16    61.9  3309.3    70.1 3309.27
    78.4 3307.74     140 3307.14   159.2 3304.29   176.9 3305.23   189.3 3301.91
   209.8 3303.21   230.3 3302.56   259.1 3305.03   271.4 3304.22   283.7 3306.11
     292  3306.6   337.1 3304.56   345.4 3305.28   353.6 3304.61   372.2 3304.87
   386.6 3304.09   394.8 3302.19  398.983300.519   415.6 3299.41  428.623300.521
   432.2  3301.8   440.9 3308.07   457.1 3322.02   461.3 3323.62     524 3336.39
#Mann= 3 ,-1,0
       0      .1       0  398.98    .045       0  428.62      .1       0
#XS Ineff= 2 , 0
          292.41 3306.73
Permanent Ineff=
       F       F
Bank Sta=398.98,428.62
XS Rating Curve= 0 ,0
Exp/Cntr(USF)=0,0
Exp/Cntr=0.3,0.1

Type RM Length L Ch R = 1 ,5742    ,224.9,217.9,210.7
XS GIS Cut Line= 4
2200138.22977307514048.4870826292200152.68507189514337.593058987
2200098.47770132514482.1460471662200111.12608779514545.387979494
#Sta/Elev= 30
       0 3311.47     4.7 3309.99    36.7    3306    72.8 3306.12    76.8 3305.87
    84.8  3303.7   120.8 3302.35   128.9 3302.79   148.9 3301.07   176.9 3300.15
   209.5 3300.66     217 3299.99     229 3296.85     245 3296.88   289.5 3300.05
   310.4  3300.7   314.7 3300.04  323.513294.946   331.7 3294.19  351.043294.948
   367.2 3297.16   387.3 3298.66   408.6 3297.68   429.4 3298.64   438.5 3305.24
   446.9 3308.37   463.3 3317.23   487.7 3321.82   495.9 3324.72   508.3 3327.02
#Mann= 3 ,-1,0
       0      .1       0  323.51    .045       0  351.04     .08       0
#XS Ineff= 2 , 0
          310.23 3300.97  387.46         3299.21
Permanent Ineff=
       F       F
Bank Sta=323.51,351.04
XS Rating Curve= 0 ,0
Exp/Cntr(USF)=0,0
Exp/Cntr=0.3,0.1

Type RM Length L Ch R = 1 ,5524    ,117.4,106.6,95.1
XS GIS Cut Line= 4
2199906.94499198514061.135469095 2199917.7864661514254.475090784
2199925.01411551514402.6419036672199930.43485256514523.705031267
#Sta/Elev= 30
       0 3312.59       5 3310.27    16.1 3301.99    20.1 3299.72    27.8 3297.13
    40.1 3294.87    80.9 3294.96   108.2 3296.79   124.2 3297.01   144.3 3296.48
   156.3 3295.38   176.3 3295.35   192.3 3294.26   200.4 3294.62   216.4 3292.96
   244.5  3292.6   260.4 3294.33   276.4 3292.52   284.5 3292.57  288.733291.525
   296.5 3289.71   300.5 3289.94  306.243291.526   312.5 3293.38   332.5 3295.83
   340.5  3298.8   360.5  3302.3   404.9  3308.7   433.6 3312.01   463.2 3318.71
#Mann= 5 ,-1,0
       0      .1       0  233.64     .08       0  288.73    .045       0
  306.24     .08       0  323.64      .1       0
#XS Ineff= 2 , 0
          260.18 3295.34
Permanent Ineff=
       F       F
Bank Sta=288.73,306.24
XS Rating Curve= 0 ,0
Exp/Cntr(USF)=0,0
Exp/Cntr=0.3,0.1

Type RM Length L Ch R = 1 ,5417    ,100.6,97.5,94.1
XS GIS Cut Line= 4
2199738.30088432514090.2664827922199776.30025109514335.296882304
2199900.78093533514462.3982125332199908.64287328514565.913728904
#Sta/Elev= 30
       0    3314     4.2 3312.36    15.1 3305.55    35.3  3294.9    39.4 3294.06
    43.4 3294.36    51.5 3292.42   189.1 3292.25   201.3 3292.71   221.6 3291.38
   245.8 3293.06   254.9    3292   302.9 3291.91   306.6 3291.21   312.2 3288.84
   319.9 3288.12   331.2 3288.84     357 3292.75   373.5  3297.8   379.4  3298.4
   390.7 3296.54   421.7  3305.1   448.7 3310.84   456.7 3311.35   472.8 3315.69
   484.8 3317.73   492.8 3319.94   504.9 3321.64   516.9 3321.42   529.7 3323.71
#Mann= 4 ,-1,0
       0      .1       0     200     .08       0   312.2    .045       0
   331.2      .1       0
#XS Ineff= 2 , 0
          245.07 3294.48
Permanent Ineff=
       F       F
Bank Sta=312.2,331.2
XS Rating Curve= 0 ,0
Exp/Cntr(USF)=0,0
Exp/Cntr=0.3,0.1

Type RM Length L Ch R = 1 ,5320    ,186.2,205.3,220.6
XS GIS Cut Line= 4
2199653.96480121514106.9425664432199702.53024372514418.144588578
2199818.99882937514498.7254026072199845.06759002514596.670021273
#Sta/Elev= 30
       0 3319.43    10.4 3317.56    17.9 3314.22    34.7 3303.21    50.8 3294.34
      67  3292.5   164.2 3292.49   176.3 3291.44   208.7 3291.01   263.9 3288.58
   321.8 3288.93   336.4 3287.78   352.8 3288.51   365.6 3290.02   370.5 3289.85
   378.7 3287.68   390.2 3287.16   407.23287.788   418.7 3289.21   428.8 3292.18
   436.2  3292.8     442  3294.4   447.7 3297.82   459.1 3306.94   463.3 3309.45
   467.4 3310.85   475.9  3312.9   496.4 3315.68   524.9  3323.1     558 3330.28
#Mann= 5 ,-1,0
       0      .1       0     180     .08       0     280      .1       0
   378.7    .045       0   407.2      .1       0
#XS Ineff= 2 , 0
          300.88 3293.06
Permanent Ineff=
       F       F
Bank Sta=378.7,407.2
XS Rating Curve= 0 ,0
Exp/Cntr(USF)=0,0
Exp/Cntr=0.3,0.1

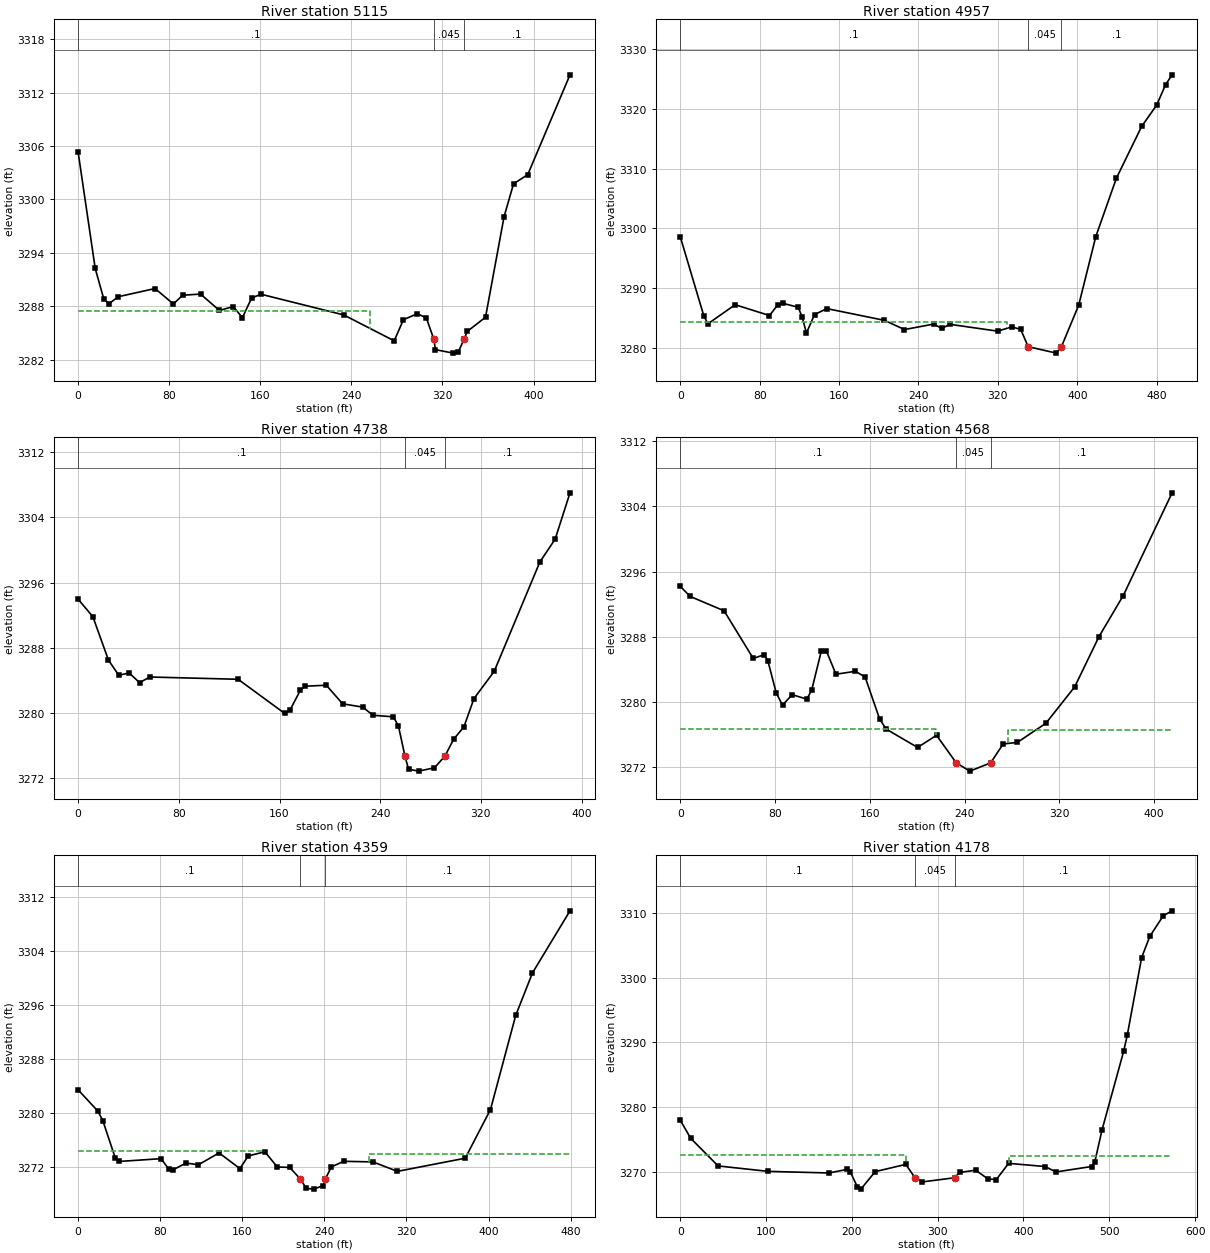
Type RM Length L Ch R = 1 ,5115    ,164,158.2,149.2
XS GIS Cut Line= 4
2199565.43855741 514162.322560822199606.99754151514455.042361882
2199608.80445386514527.3188559722199626.87357739514588.753875948
#Sta/Elev= 30
       0 3305.31      15 3292.25    22.6  3288.8    27.1 3288.29    35.2 3289.08
    67.5    3290    83.7 3288.27    91.8 3289.25   107.5 3289.38   124.1 3287.54
   136.2 3287.98   144.3 3286.74   152.4 3288.94   160.6 3289.36   233.2 3287.04
   277.6 3284.13   285.7  3286.5   297.8 3287.17   305.8 3286.71  312.43  3284.3
   313.8 3283.14   329.5 3282.75   333.8 3282.85  339.023284.339   341.8 3285.19
   357.8 3286.78   374.1 3298.07   382.4 3301.75   394.9 3302.79     432 3313.99
#Mann= 3 ,-1,0
       0      .1       0  312.43    .045       0  339.02      .1       0
#XS Ineff= 2 , 0
           256.6 3287.44
Permanent Ineff=
       F       F
Bank Sta=312.43,339.02
XS Rating Curve= 0 ,0
Exp/Cntr(USF)=0,0
Exp/Cntr=0.3,0.1

Type RM Length L Ch R = 1 ,4957    ,210.3,218.3,227
XS GIS Cut Line= 4
2199375.71276043514182.1985966942199458.83072863 514502.02208304
2199494.96897567514572.491664778 2199516.6519239514655.609632981
#Sta/Elev= 30
       0 3298.62    23.7 3285.41    27.9 3284.06    55.3 3287.25    89.9 3285.44
    98.1  3287.2     104 3287.46   118.8 3286.82   122.9 3285.17   127.1 3282.52
   135.3  3285.6   147.7  3286.6   205.6 3284.64   225.9  3283.1   255.2 3284.01
   263.5 3283.29   271.7 3283.97   319.9 3282.83   333.8 3283.55     343 3283.13
  350.453280.243   378.9 3279.16  384.033280.246   401.4 3287.17   418.6 3298.62
   439.3 3308.36   464.8 3317.03     480 3320.62   488.9 3324.01   495.5 3325.66
#Mann= 3 ,-1,0
       0      .1       0  350.45    .045       0  384.03      .1       0
#XS Ineff= 2 , 0
          329.48 3284.36
Permanent Ineff=
       F       F
Bank Sta=350.45,384.03
XS Rating Curve= 0 ,0
Exp/Cntr(USF)=0,0
Exp/Cntr=0.3,0.1

Type RM Length L Ch R = 1 ,4738    ,167.8,170.1,172.2
XS GIS Cut Line= 4
2199216.70447343514297.840987238 2199274.5256687514529.125768324
2199276.33258105514610.4368241752199285.36714281514680.906405912
#Sta/Elev= 30
       0 3293.96    11.7 3291.82    24.1 3286.48    32.3 3284.62    40.5 3284.91
    48.8 3283.72      57 3284.41   127.1 3284.13   164.2 3279.93   168.4 3280.37
   176.6 3282.79   180.4 3283.28   197.2  3283.4   210.1 3281.12   226.1 3280.71
   234.3 3279.71   250.5 3279.52   254.5 3278.38  259.683274.692   262.5 3273.09
   270.5 3272.85   283.1 3273.26  291.413274.692   298.5  3276.8   306.5 3278.28
   314.5 3281.76   330.6 3285.11   366.9 3298.55     379 3301.34   390.8 3307.03
#Mann= 3 ,-1,0
       0      .1       0  259.68    .045       0  291.41      .1       0
Bank Sta=259.68,291.41
XS Rating Curve= 0 ,0
Exp/Cntr(USF)=0,0
Exp/Cntr=0.3,0.1

Type RM Length L Ch R = 1 ,4568    ,213.1,208.7,204.9
XS GIS Cut Line= 4
2199079.37913466514305.068636646 2199115.5173817514464.076923643
2199102.86899524514624.8921229922199122.74503111514713.430828252
#Sta/Elev= 30
       0 3294.19     8.3 3292.95      37 3291.18    61.6 3285.33    70.9 3285.79
    73.9 3285.07      81 3281.09    86.3  3279.6    94.5 3280.88   106.8 3280.33
   110.9 3281.43   119.1 3286.27   123.2  3286.3   131.4 3283.39   147.8 3283.75
     156 3283.06   168.2 3277.92   173.7 3276.66   200.3  3274.4   216.3 3275.89
   232.93272.508   244.4 3271.49  261.973272.507   272.5 3274.82   284.5 3275.02
   308.6 3277.37   332.9 3281.84   353.4 3288.01   373.9 3293.06   415.1 3305.67
#Mann= 3 ,-1,0
       0      .1       0   232.9    .045       0  261.97      .1       0
#XS Ineff= 2 , 0
          216.17 3276.61  276.68         3276.48
Permanent Ineff=
       F       F
Bank Sta=232.9,261.97
XS Rating Curve= 0 ,0
Exp/Cntr(USF)=0,0
Exp/Cntr=0.3,0.1

Type RM Length L Ch R = 1 ,4359    ,210.7,181.2,166.3
XS GIS Cut Line= 3
2198866.16347709514321.330847817 2198907.7224612514592.367700652
2198951.08835765514792.934971751
#Sta/Elev= 30
       0 3283.47    19.2 3280.33    24.1 3278.89    36.3 3273.33    40.3 3272.87
    80.8 3273.28    88.2 3271.76    92.9 3271.66   105.1 3272.63   117.2 3272.38
   137.4 3274.13   157.7 3271.81   165.8 3273.69     182  3274.3   194.1 3272.05
   206.2 3271.98  216.663270.262   222.4 3268.88   229.7 3268.77   238.6 3269.28
  241.013270.262   246.7 3272.05   258.8 3272.89   287.3  3272.8   311.2  3271.4
   377.3 3273.35   401.9 3280.56   426.5  3294.5   442.8 3300.78   479.4 3309.98
#Mann= 3 ,-1,0
       0      .1       0  216.66    .045       0  241.01      .1       0
#XS Ineff= 2 , 0
          181.52 3274.39  283.28         3273.94
Permanent Ineff=
       F       F
Bank Sta=216.66,241.01
XS Rating Curve= 0 ,0
Exp/Cntr(USF)=0,0
Exp/Cntr=0.3,0.1

Type RM Length L Ch R = 1 ,4178    ,266.1,274.1,292.7
XS GIS Cut Line= 4
2198616.80957249514326.7515848732198685.47224187514567.070927721
2198819.18375594 514655.609632982198867.97038945514811.004095273
#Sta/Elev= 30
       0 3277.96    12.3 3275.14    44.1 3270.88   102.4 3270.04   173.4 3269.79
   193.9 3270.33     198 3270.01   206.4 3267.64   210.5 3267.29   227.2    3270
   262.8 3271.12   273.6 3269.05   282.3 3268.41   319.8 3269.05   325.6 3269.87
   344.3 3270.22   358.7 3268.86   368.3 3268.77   382.7 3271.28   425.1 3270.79
   437.9 3269.95   479.4 3270.79   483.2 3271.56   491.6 3276.49   516.8 3288.66
     521 3291.15   537.7 3303.14   547.2 3306.41   562.9 3309.61   573.2 3310.37
#Mann= 3 ,-1,0
       0      .1       0   273.6    .045       0   319.8      .1       0
#XS Ineff= 2 , 0
          262.71 3272.64  382.84         3272.36
Permanent Ineff=
       F       F
Bank Sta=273.6,319.8
XS Rating Curve= 0 ,0
Exp/Cntr(USF)=0,0
Exp/Cntr=0.3,0.1