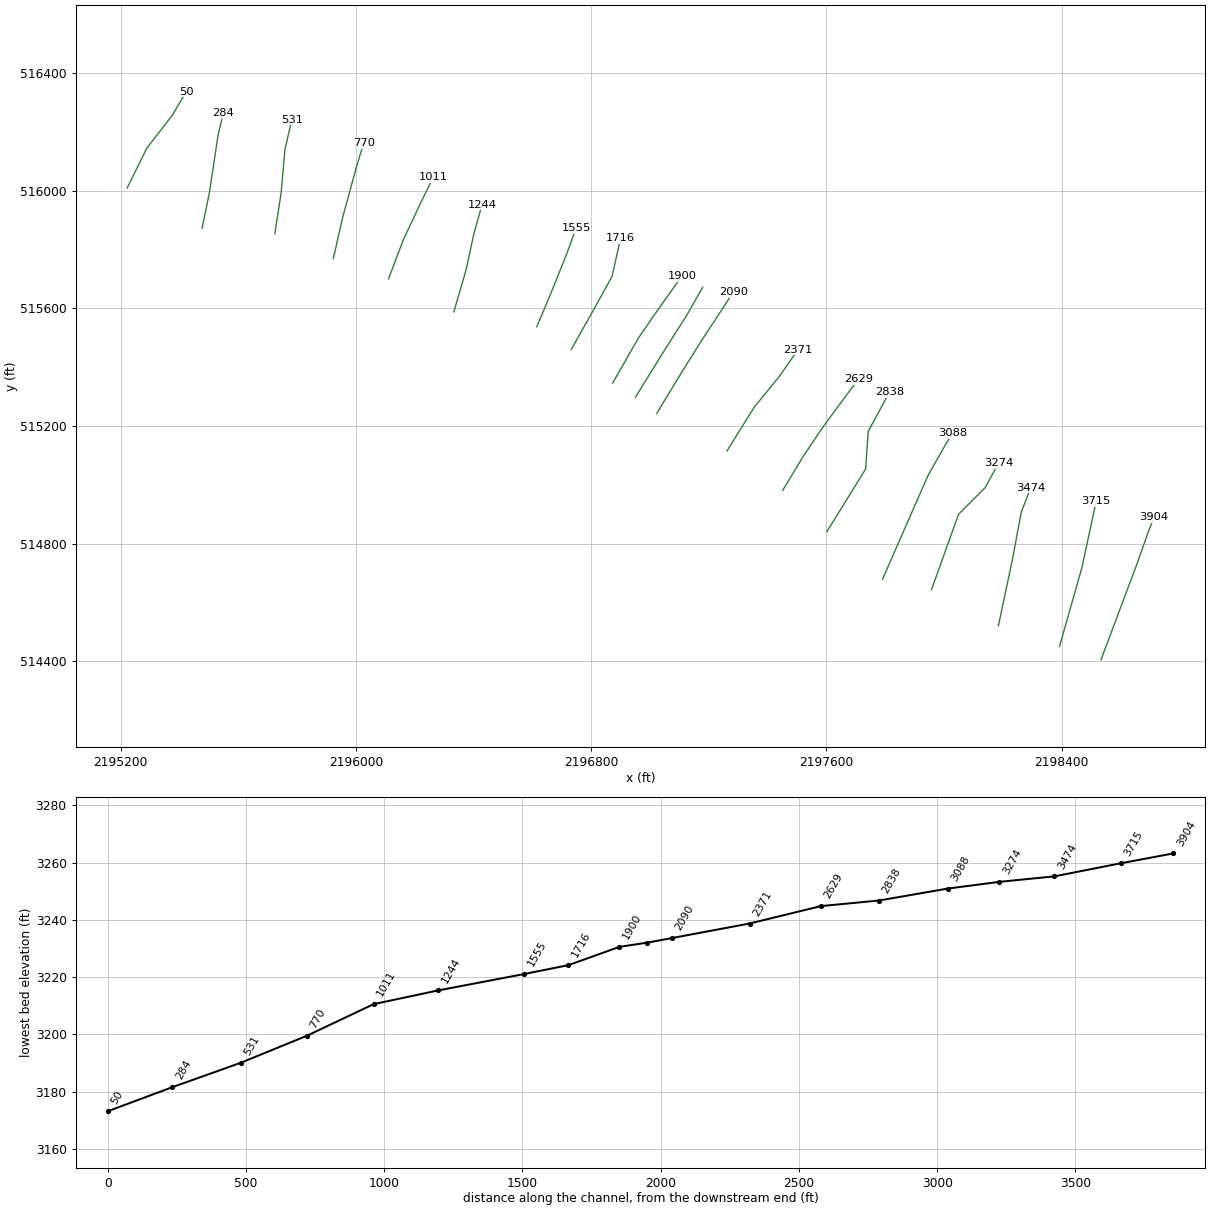
HEC-RAS study NFGAULYRV.prj: NFGAULYRV

--- NFGAULYRV.g01 (geometry) --- (continued)

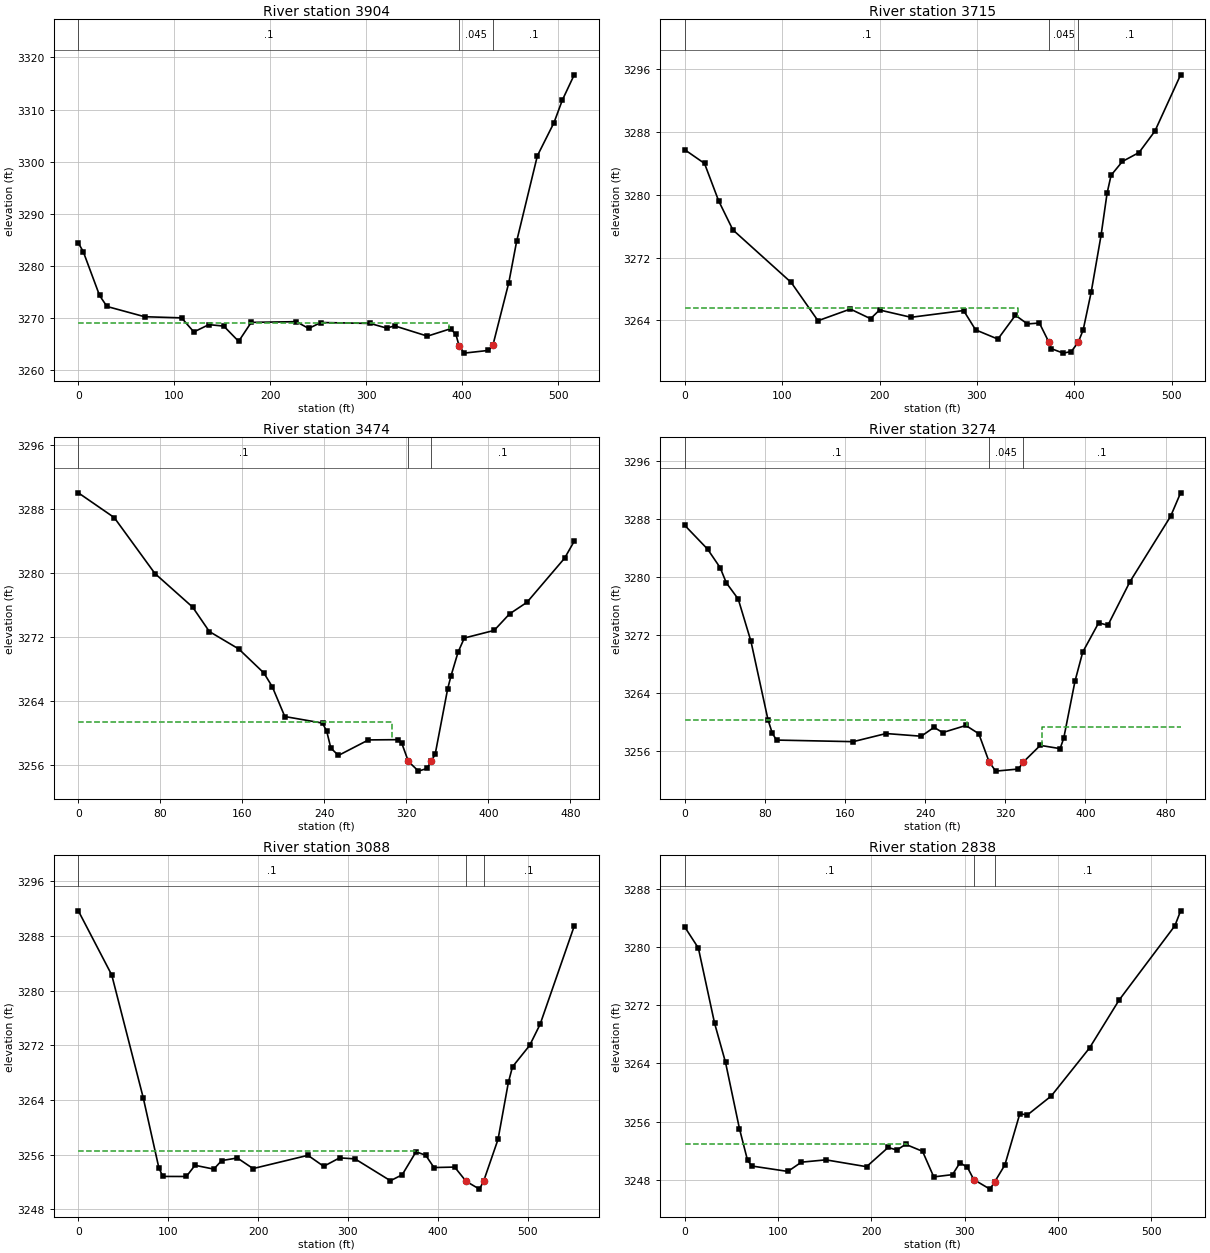
Type RM Length L Ch R = 1 ,3904    ,186.8,189.1,192.9
XS GIS Cut Line= 4
2198533.69160428 514404.448816022198656.56164424514731.499951774
2198698.12062834 514848.949254672198714.38283951514888.701326419
#Sta/Elev= 30
       0 3284.36     5.1 3282.73    22.1 3274.31    29.8 3272.19    69.1 3270.22
   107.6    3270   120.4  3267.3   136.1  3268.7   151.6 3268.42   167.1 3265.49
   180.2 3269.13   227.2 3269.27   240.1 3267.97   252.9 3269.11   304.2 3268.93
   321.3 3268.04   329.8 3268.46   363.9 3266.49     388 3267.91   393.6 3266.81
  396.78 3264.69   402.1 3263.23   427.5 3263.75   432.1 3264.72   448.7 3276.76
   456.9 3284.71   478.5 3301.12   495.8 3307.47   504.5  3311.8   516.9 3316.66
#Mann= 3 ,-1,0
       0      .1       0  396.78    .045       0   432.1      .1       0
#XS Ineff= 2 , 0
          386.14    3269
Permanent Ineff=
       F       F
Bank Sta=396.78,432.1
XS Rating Curve= 0 ,0
Exp/Cntr(USF)=0,0
Exp/Cntr=0.3,0.1

Type RM Length L Ch R = 1 ,3715    ,240.8,241.4,242.7
XS GIS Cut Line= 4
2198392.75244081514449.621624825 2198468.6427596514717.044652956
2198502.97409429514876.0529399532198517.42939311514942.908696986
#Sta/Elev= 30
       0 3285.75    20.3    3284    34.8 3279.23    49.4 3275.53   109.3 3268.82
   136.8 3263.94     170 3265.43   190.8  3264.2     200 3265.31   232.3 3264.38
   286.3 3265.24   298.6 3262.78   321.5  3261.6   339.5 3264.64   351.8 3263.53
   364.1 3263.65  373.76 3261.23   376.3 3260.38   388.6 3259.81   396.8 3260.01
     404 3261.19   409.1 3262.79   417.3  3267.6   427.4 3274.82   433.6  3280.2
   437.7 3282.49   449.3 3284.25   466.4 3285.39   482.7 3288.12   509.1  3295.3
#Mann= 3 ,-1,0
       0      .1       0  373.76    .045       0     404      .1       0
#XS Ineff= 2 , 0
          341.91 3265.57
Permanent Ineff=
       F       F
Bank Sta=373.76,404
XS Rating Curve= 0 ,0
Exp/Cntr(USF)=0,0
Exp/Cntr=0.3,0.1

Type RM Length L Ch R = 1 ,3474    ,211.9,199.5,189.2
XS GIS Cut Line= 4
 2198184.9575203514520.0912065632198233.74415381514751.375987649
2198262.65475145514906.7704499412198295.17917379514989.888418144
#Sta/Elev= 30
       0 3289.98      35 3286.89    74.7  3279.9   111.5  3275.7   127.8 3272.65
   156.5 3270.47     181 3267.47   189.2 3265.75   201.4 3262.03   238.2 3261.21
   242.3 3260.18   246.3 3258.09   253.7 3257.17     283 3259.11   311.4 3259.14
   315.5 3258.69  321.943256.419   331.8 3255.21   339.9 3255.54   344.23256.418
   348.1 3257.34   360.3 3265.52   363.5  3267.1   370.4 3270.07   376.5 3271.84
   405.6 3272.79   420.6 3274.85   437.6  3276.3   474.3 3281.81   483.7 3283.93
#Mann= 3 ,-1,0
       0      .1       0  321.94    .045       0   344.2      .1       0
#XS Ineff= 2 , 0
          305.83 3261.36
Permanent Ineff=
       F       F
Bank Sta=321.94,344.2
XS Rating Curve= 0 ,0
Exp/Cntr(USF)=0,0
Exp/Cntr=0.3,0.1

Type RM Length L Ch R = 1 ,3274    ,184,186.2,189.4
XS GIS Cut Line= 4
2197957.28656392514642.9612465152198049.43909388514899.542800532
 2198139.7847115514989.888418144 2198184.9575203515073.006386347
#Sta/Elev= 30
       0 3287.15    22.8 3283.87    35.3 3281.33    41.5 3279.23    53.4 3276.99
    66.1 3271.16    83.1 3260.36    87.4  3258.5    91.6 3257.56   168.1 3257.34
     201 3258.46   236.1 3258.09   248.9 3259.32   257.4 3258.59   280.6 3259.57
   293.5 3258.44  303.843254.558   310.4 3253.28   333.1 3253.57  338.153254.556
   354.9 3256.83   374.7 3256.38   378.3 3257.81   389.6  3265.7   397.3 3269.69
   413.2 3273.72   422.4 3273.38   444.4 3279.38     485 3288.39     495 3291.63
#Mann= 3 ,-1,0
       0      .1       0  303.84    .045       0  338.15      .1       0
#XS Ineff= 2 , 0
          281.63  3260.3  356.44         3259.32
Permanent Ineff=
       F       F
Bank Sta=303.84,338.15
XS Rating Curve= 0 ,0
Exp/Cntr(USF)=0,0
Exp/Cntr=0.3,0.1

Type RM Length L Ch R = 1 ,3088    ,242.6,249.8,256
XS GIS Cut Line= 4
2197791.05062751 514679.099493562197946.44508981515033.254314598
2198006.07319743515138.0552310282198029.56305801515176.000390425
#Sta/Elev= 30
       0  3291.7    37.2  3282.3    72.3 3264.29    89.6 3254.08      94  3252.8
   120.2 3252.79   129.9 3254.43   150.8 3253.87   159.5 3255.12     177  3255.5
   194.5 3253.95   255.6 3255.89   273.1 3254.28   290.9 3255.52     308 3255.37
   347.4 3252.17   360.5 3253.04   375.9 3256.41   386.7  3255.9   395.9  3254.1
   418.9 3254.17   431.6 3252.09   446.5 3250.94   451.1 3252.09   467.2 3258.23
   478.7 3266.57   483.3 3268.86   502.4 3271.99     514 3275.07     552 3289.46
#Mann= 3 ,-1,0
       0      .1       0   431.6    .045       0   451.1      .1       0
#XS Ineff= 2 , 0
          377.56 3256.52
Permanent Ineff=
       F       F
Bank Sta=431.6,451.1
XS Rating Curve= 0 ,0
Exp/Cntr(USF)=0,0
Exp/Cntr=0.3,0.1

Type RM Length L Ch R = 1 ,2838    ,217.2,208.8,201.4
XS GIS Cut Line= 4
2197601.32483053514839.9146929092197733.22943224515053.130350473
  2197742.263994515181.4211274812197814.54048809515315.132641547
#Sta/Elev= 30
       0 3282.74    14.6 3279.85      32 3269.51    43.7 3264.15    58.6 3255.06
    67.3  3250.7      72 3249.92   110.5 3249.18     125 3250.45   151.2 3250.77
   194.8 3249.83   217.9 3252.47   227.3 3252.12   236.7  3252.9   254.8 3251.94
   266.8 3248.43   286.9 3248.74   294.9 3250.38   302.9 3249.73   309.7 3248.06
     327 3246.75   332.2 3247.77     343 3250.07     359  3257.1   367.1 3256.93
   392.7 3259.54   433.7 3266.13   465.4 3272.71   525.2 3282.92   531.3 3284.96
#Mann= 3 ,-1,0
       0      .1       0   309.7    .045       0   332.2      .1       0
#XS Ineff= 2 , 0
          237.62 3252.88
Permanent Ineff=
       F       F
Bank Sta=309.7,332.2
XS Rating Curve= 0 ,0
Exp/Cntr(USF)=0,0
Exp/Cntr=0.3,0.1

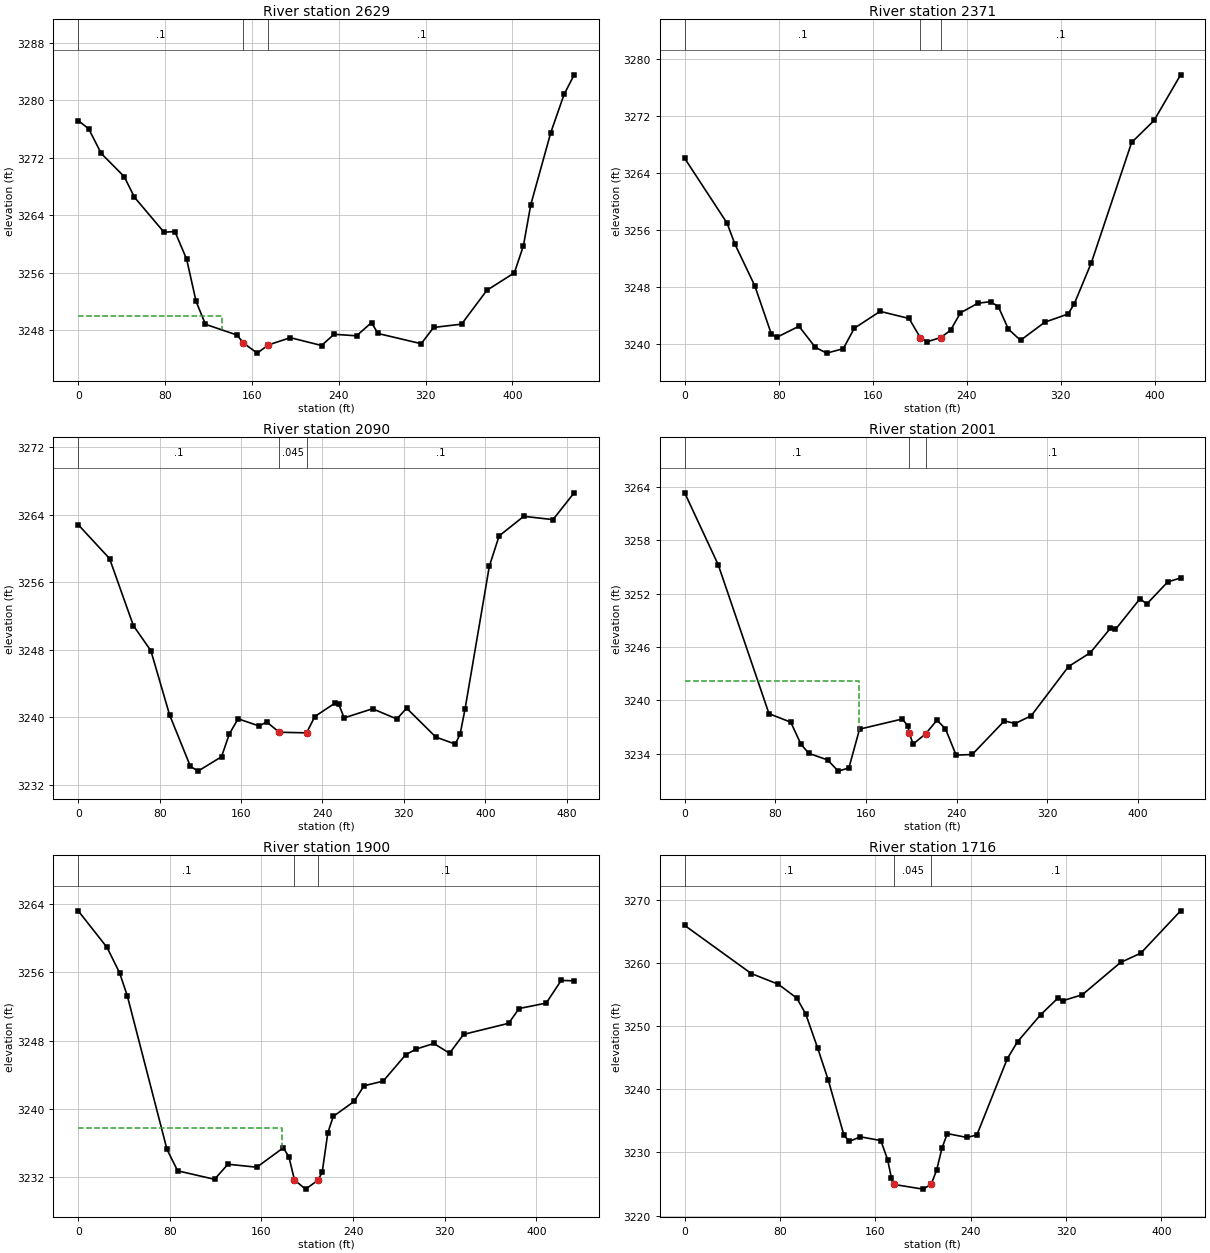
Type RM Length L Ch R = 1 ,2629    ,258.6,258,255.4
XS GIS Cut Line= 4
2197451.35110529514980.8538563832197520.01377468515094.689334574
2197590.48335642515199.4902510042197707.93265931515358.498538001
#Sta/Elev= 30
       0 3277.16     9.6 3276.02    21.2 3272.59    42.4 3269.36    51.8  3266.5
      79 3261.64    89.1 3261.72    99.9 3257.88   108.6 3252.01   117.2 3248.83
   146.4 3247.33   152.1 3246.24   164.9 3244.82   175.2 3245.96   195.4 3246.97
   224.2 3245.88   235.7 3247.44   256.4 3247.23   270.2 3249.06   276.2 3247.55
     316 3246.13   327.4 3248.39   353.2 3248.85   376.5 3253.56   401.8 3255.98
   410.2 3259.77   416.9 3265.44   435.4  3275.5   447.6 3280.79   456.9 3283.52
#Mann= 3 ,-1,0
       0      .1       0   152.1    .045       0   175.2      .1       0
#XS Ineff= 2 , 0
          132.01    3250
Permanent Ineff=
       F       F
Bank Sta=152.1,175.2
XS Rating Curve= 0 ,0
Exp/Cntr(USF)=0,0
Exp/Cntr=0.3,0.1

Type RM Length L Ch R = 1 ,2371    ,279.3,281.4,282.1
XS GIS Cut Line= 4
2197261.62530831515114.5653704492197353.77783827515262.732183332
2197440.50963118515369.3400121142197503.75156351515459.685629726
#Sta/Elev= 30
       0 3266.06    36.1 3256.96    42.7 3254.04    59.6 3248.21    73.7 3241.45
    78.4 3240.95    97.3  3242.5   111.2 3239.55   120.8 3238.73     135 3239.35
   144.4 3242.22   166.4 3244.59     191 3243.59   200.7 3240.87   206.4 3240.32
  218.01 3240.92   226.3 3241.93   234.8 3244.39   249.8 3245.74   260.4 3245.94
     267 3245.26   275.6 3242.09   285.9 3240.53   306.6 3243.07   326.4 3244.22
   331.7 3245.66   346.2 3251.41   380.5 3268.28   399.6 3271.37   422.2 3277.77
#Mann= 3 ,-1,0
       0      .1       0   200.7    .045       0  218.01      .1       0
Bank Sta=200.7,218.01
XS Rating Curve= 0 ,0
Exp/Cntr(USF)=0,0
Exp/Cntr=0.3,0.1

Type RM Length L Ch R = 1 ,2090    ,89.9,89.4,89.2
XS GIS Cut Line= 4
2197023.11287781515242.8561474572197115.26540778515394.636785045
2197173.08660305515486.7893150092197283.30825654515654.832163768
#Sta/Elev= 30
       0  3262.8    30.8 3258.79    54.2 3250.86    71.4 3247.89    89.8 3240.29
   110.2 3234.21   117.7 3233.64   140.8 3235.34   148.5 3238.04   157.1 3239.83
   177.6 3238.99   185.3 3239.45   197.5 3238.24   224.4 3238.17   232.5  3240.1
   252.6 3241.71   256.1 3241.53   261.3 3239.94   289.2 3241.02   313.1 3239.81
   322.7 3241.09   351.4 3237.67   370.5 3236.84   375.3 3238.03   380.1 3240.98
     404  3257.9   413.6 3261.47   437.8 3263.79   466.5  3263.4487.3216 3266.57
#Mann= 3 ,-1,0
       0      .1       0   197.5    .045       0   224.4      .1       0
Bank Sta=197.5,224.4
XS Rating Curve= 0 ,0
Exp/Cntr(USF)=0,0
Exp/Cntr=0.3,0.1

Type RM Length L Ch R = 1 ,2001    ,101.3,100.3,99.7
XS GIS Cut Line= 4
2196950.65842599515297.9090167842197042.86516332515447.196115327
2197124.82670762515575.9928277952197178.97987082515671.126763141
#Sta/Elev= 30
       0 3263.32    29.6 3255.23    74.4 3238.49    93.6 3237.53   102.6 3235.06
   109.5 3234.03   126.1 3233.29   135.5 3232.03   144.9 3232.39   154.3 3236.75
     192 3237.89   196.8 3237.13   198.1 3236.35   201.5 3235.07   212.6 3236.22
   222.6 3237.76   230.1 3236.79   239.5 3233.83   253.7  3233.9   282.1 3237.68
   291.6 3237.38   305.8 3238.26   338.7 3243.79   357.9 3245.34   375.5 3248.07
   380.1 3247.96   401.8 3251.42   407.7 3250.81   426.2  3253.3   437.6 3253.75
#Mann= 3 ,-1,0
       0      .1       0   198.1    .045       0   212.6      .1       0
#XS Ineff= 2 , 0
          153.49 3242.13
Permanent Ineff=
       F       F
Bank Sta=198.1,212.6
XS Rating Curve= 0 ,0
Exp/Cntr(USF)=0,0
Exp/Cntr=0.3,0.1

Type RM Length L Ch R = 1 ,1900    ,182.1,184.3,187.2
XS GIS Cut Line= 4
2196873.13915258515345.8501515352196959.87094548515497.630789123
2197010.46449135515571.7141955652197108.03775837515709.039534335
#Sta/Elev= 30
       0 3263.21    25.2 3258.91    36.1 3255.94    42.8 3253.27    77.5 3235.23
    86.8 3232.72     119 3231.72   130.7 3233.49   155.9 3233.14   179.1 3235.42
     184 3234.33   188.8 3231.64   198.5 3230.57   209.2  3231.6     213 3232.54
   217.9 3237.17   222.7  3239.1   240.9 3240.86   249.5 3242.69   266.3 3243.24
   285.9 3246.33   295.1    3247   310.5 3247.65   324.2 3246.51   336.5 3248.72
   375.8 3250.02   384.9 3251.75   408.6 3252.39   421.7 3255.05432.9846    3255
#Mann= 3 ,-1,0
       0      .1       0   188.8    .045       0   209.2      .1       0
#XS Ineff= 2 , 0
          178.22 3237.69
Permanent Ineff=
       F       F
Bank Sta=188.8,209.2
XS Rating Curve= 0 ,0
Exp/Cntr(USF)=0,0
Exp/Cntr=0.3,0.1

Type RM Length L Ch R = 1 ,1716    ,158.1,160.7,163.4
XS GIS Cut Line= 4
2196732.48580554515460.7434964572196801.63924124 515583.43507593
2196870.79267694515708.3574113942196899.79250482515837.741258839
#Sta/Elev= 30
       0 3265.92    55.9  3258.3    78.6 3256.61    94.1 3254.41   101.5 3251.94
   111.7 3246.45   120.5 3241.44   133.7 3232.69   138.2 3231.73   147.4 3232.46
   164.6 3231.87   170.3 3228.85   173.4 3226.01   175.53224.927   199.9 3224.18
   206.8 3224.92   211.4 3227.16     216 3230.71   220.4 3232.97   236.9 3232.36
   245.2 3232.75   270.8 3244.85   279.4 3247.53   298.7 3251.78   313.2 3254.41
   317.3    3254   333.7 3254.95   365.8 3260.06   382.8 3261.53   416.2 3268.23
#Mann= 3 ,0,0
       0      .1       0   175.5    .045       0   206.8      .1       0
Bank Sta=175.5,206.8
XS Rating Curve= 0 ,0
Exp/Cntr(USF)=0,0
Exp/Cntr=0.3,0.1

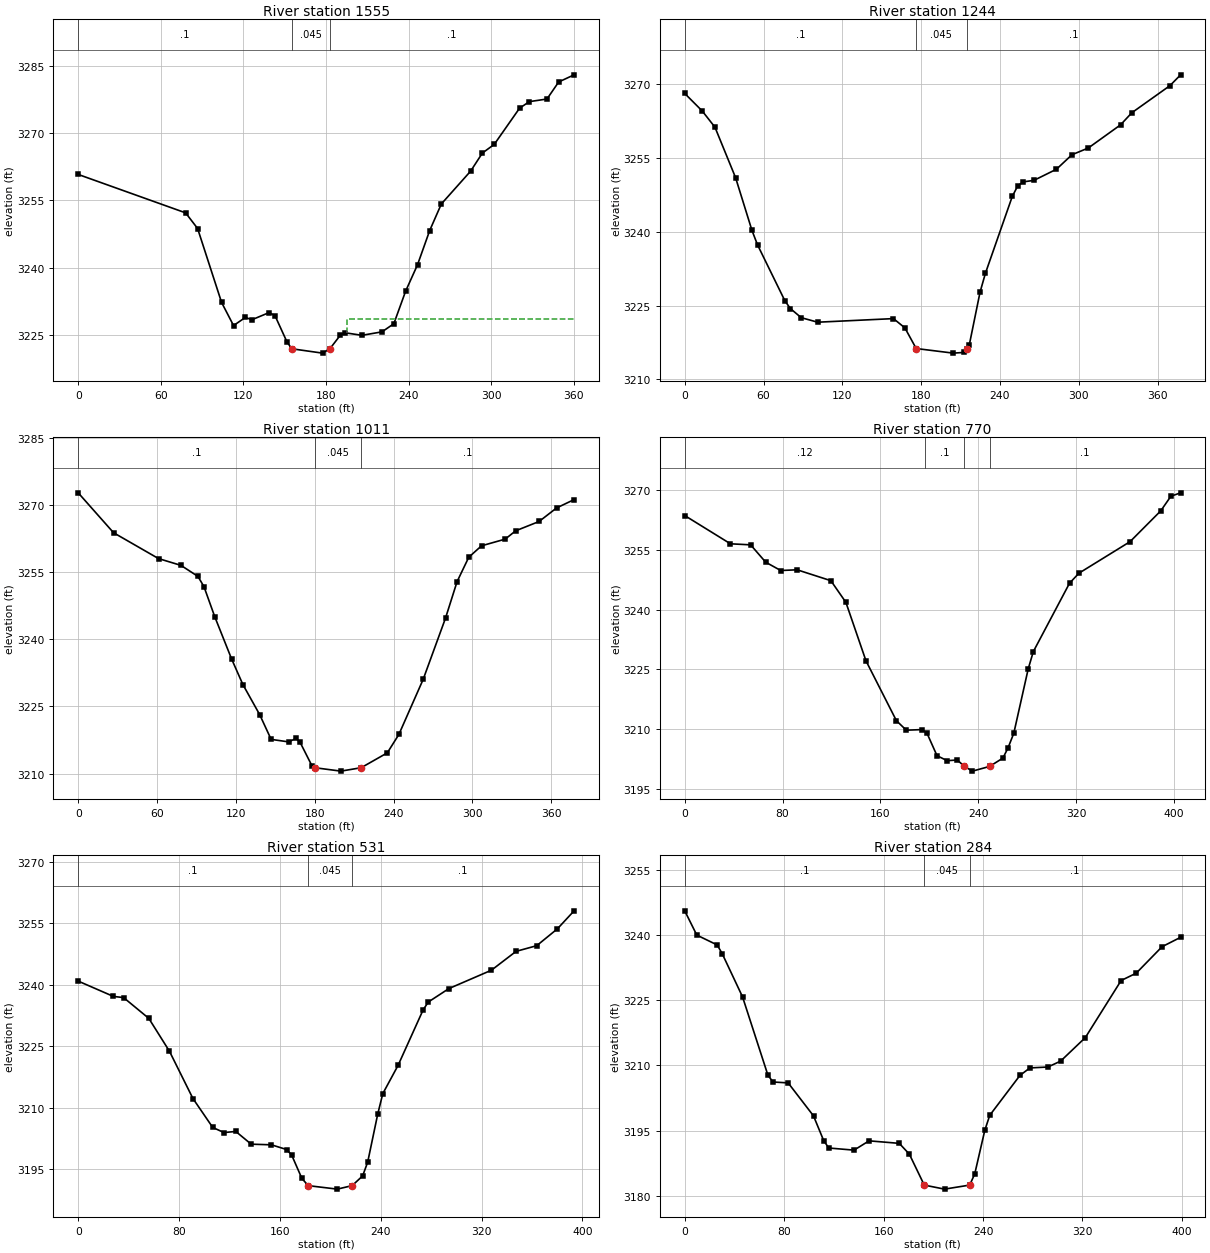
Type RM Length L Ch R = 1 ,1555    ,306.8,311.2,314.3
XS GIS Cut Line= 4
2196614.75068621515537.3828608722196656.30967031515634.956127893
2196715.93777793515783.1229407762196748.46220027515871.661646036
#Sta/Elev= 30
       0 3260.79      78 3252.25    86.7 3248.77   104.1 3232.34   112.8 3227.19
   121.4    3229   126.1 3228.48   138.6 3230.07   142.9 3229.39   151.6 3223.55
  155.133222.026   177.4 3221.06  182.753222.026   190.4 3225.07   193.7 3225.59
     206 3225.02   220.6 3225.79   229.2  3227.6   237.8 3234.87   246.4 3240.71
   255.2 3248.29   263.7 3254.23     285 3261.54   293.5 3265.55   302.1 3267.47
   320.5 3275.52   327.6 3276.98   340.4 3277.56   348.9 3281.35360.0938 3282.94
#Mann= 3 ,-1,0
       0      .1       0  155.13    .045       0  182.75      .1       0
#XS Ineff= 2 , 0
                          195.38         3228.59
Permanent Ineff=
       F       F
Bank Sta=155.13,182.75
XS Rating Curve= 0 ,0
Exp/Cntr(USF)=0,0
Exp/Cntr=0.3,0.1

Type RM Length L Ch R = 1 ,1244    ,237.5,232.8,227.7
XS GIS Cut Line= 4
2196332.87235926515587.9764067352196374.43134336515730.722482561
2196399.72811629515848.1717854572196428.63871393515952.972701887
#Sta/Elev= 30
       0 3268.14    13.3 3264.58      23 3261.28    38.7 3251.02    51.2 3240.27
    55.4 3237.36    76.2    3226    80.4  3224.4    88.7 3222.54   101.2 3221.62
   158.9 3222.35   167.6 3220.47  176.213216.265   204.4 3215.33   212.6 3215.47
  214.643216.263   216.7 3217.08   224.8  3227.7   228.9 3231.56   249.4 3247.22
   253.5 3249.33   257.6 3250.16   265.8 3250.46     283 3252.73   294.8 3255.68
   307.2 3257.04   331.8 3261.76   340.4 3264.22   369.4 3269.73377.5309 3271.93
#Mann= 3 ,-1,0
       0      .1       0  176.21    .045       0  214.64      .1       0
Bank Sta=176.21,214.64
XS Rating Curve= 0 ,0
Exp/Cntr(USF)=0,0
Exp/Cntr=0.3,0.1

Type RM Length L Ch R = 1 ,1011    ,240.6,241.8,243.2
XS GIS Cut Line= 4
2196110.62213993515700.004972573 2196161.2156858515833.716486639
2196220.84379342515960.2003512962196262.40277752516045.125231851
#Sta/Elev= 30
       0 3272.69    26.9 3263.78    61.1 3258.01    78.2 3256.49    91.1 3254.03
    95.7 3251.74   103.9 3245.03   116.7 3235.61   125.3 3229.89   138.1 3223.16
   146.8 3217.64   160.1 3217.08   165.8 3217.85   168.9 3216.95   177.8 3211.78
  180.023211.313   199.9 3210.55  215.323211.312   235.2 3214.63     244 3218.73
   262.5 3231.04   279.5 3244.71   288.3 3252.86   297.2 3258.31   306.9 3260.86
   324.9 3262.35   332.9 3264.21   350.7 3266.29     364 3269.31 377.346 3271.18
#Mann= 3 ,-1,0
       0      .1       0  180.02    .045       0  215.32      .1       0
Bank Sta=180.02,215.32
XS Rating Curve= 0 ,0
Exp/Cntr(USF)=0,0
Exp/Cntr=0.3,0.1

Type RM Length L Ch R = 1 ,770     ,232.8,238.8,240.8
XS GIS Cut Line= 4
 2195922.7032553515768.6676419582195955.22767764515911.413717785
 2196002.2073988516083.0703912482196025.69725938516160.767622394
#Sta/Elev= 30
       0  3263.6    37.4 3256.51    53.9 3256.25    66.2  3251.9    78.5 3249.81
    91.9 3249.99   119.5 3247.26   131.8 3241.82   148.2 3227.17   173.1 3212.14
   181.2 3209.75   193.9  3209.9     198 3209.07   206.3 3203.36   214.6  3202.1
   222.9 3202.27  228.743200.659   235.3 3199.48  249.313200.659   260.2 3202.75
   264.4 3205.31   269.1 3208.97   280.9 3225.13   285.1 3229.48   314.7 3246.63
   322.4 3249.14   364.2 3257.05   389.3 3264.78   397.6 3268.45405.5443  3269.3
#Mann= 4 ,-1,0
       0     .12       0   196.4      .1       0  228.74    .045       0
  249.31      .1       0
Bank Sta=228.74,249.31
XS Rating Curve= 0 ,0
Exp/Cntr(USF)=0,0
Exp/Cntr=0.3,0.1

Type RM Length L Ch R = 1 ,531     ,246.7,247.1,244.7
XS GIS Cut Line= 4
2195723.94289656515853.5925225142195745.62584478515994.531685988
2195758.27423125516139.0846741672195781.76409183516242.078678245
#Sta/Elev= 30
       0  3240.9    27.9 3237.16      36 3236.87      56 3231.79    72.4 3223.74
      91  3212.2   106.7 3205.13   115.6 3203.88     125 3204.15   137.2 3201.04
   153.3 3200.88   165.3 3199.73   169.3 3198.39   177.4 3192.68  182.433190.903
   205.5 3190.05  217.293190.905   225.6 3193.28   229.6 3196.63   237.6 3208.42
   241.6 3213.39   253.7 3220.29   273.7 3233.94   277.8 3235.81     294 3239.07
   327.8 3243.57   347.3 3248.17   363.7 3249.56   380.1 3253.68393.3413 3258.08
#Mann= 3 ,-1,0
       0      .1       0  182.43    .045       0  217.29      .1       0
Bank Sta=182.43,217.29
XS Rating Curve= 0 ,0
Exp/Cntr(USF)=0,0
Exp/Cntr=0.3,0.1

Type RM Length L Ch R = 1 ,284     ,242.1,234.1,219.6
XS GIS Cut Line= 4
 2195476.3959043515871.6616460362195501.69267723515994.531685988
2195530.60327487516187.8713076772195548.67239839516263.761626471
#Sta/Elev= 30
       0 3245.57     9.7 3239.99    26.1 3237.72    30.1 3235.74    46.5 3225.78
    66.9 3207.77      71 3206.19    83.2 3205.98   103.6 3198.39   111.8 3192.69
   115.9    3191   136.2 3190.51   148.3 3192.65   172.6 3192.07   180.7 3189.59
  192.693182.469     209 3181.54  229.25 3182.47   233.3 3185.03   241.4 3195.07
   245.4 3198.53   269.7 3207.71   277.7 3209.43   292.1 3209.63   302.4 3210.99
   322.3 3216.41   351.1 3229.54   363.2 3231.22     384 3237.31398.9481 3239.48
#Mann= 3 ,-1,0
       0      .1       0  192.69    .045       0  229.25      .1       0
Bank Sta=192.69,229.25
XS Rating Curve= 0 ,0
Exp/Cntr(USF)=0,0
Exp/Cntr=0.3,0.1

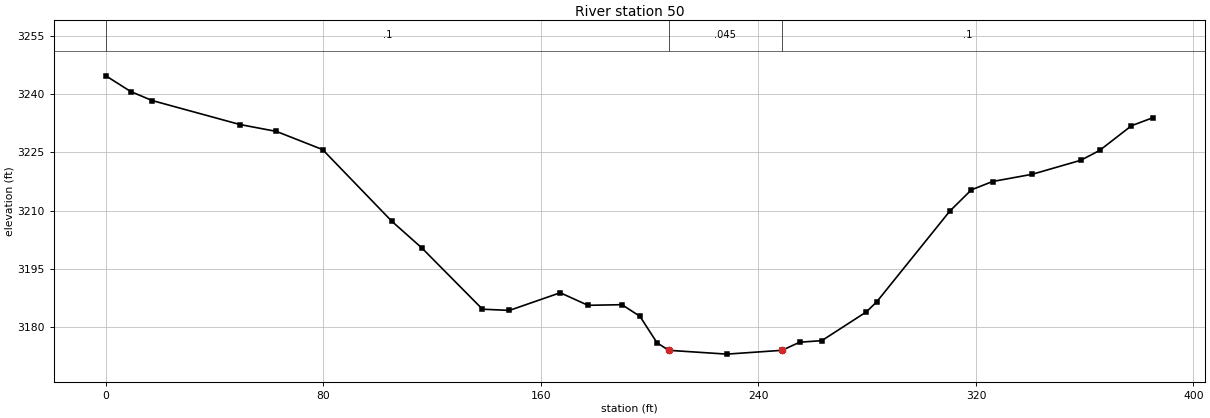
Type RM Length L Ch R = 1 ,50      ,,,
XS GIS Cut Line= 4
2195221.62126263516008.9869848062195288.47701967516144.505411224
2195375.20881257516256.5339770632195422.18853373516336.038120561
#Sta/Elev= 30
       0 3244.66     9.1 3240.63      17 3238.31    49.3 3232.14    62.7 3230.37
    79.7  3225.7   105.2 3207.24   116.2 3200.41   138.5 3184.66   148.4 3184.35
   167.1 3188.89   177.3 3185.66   189.8 3185.82   196.4 3182.84   202.7 3176.03
  206.99 3174.09   228.4 3173.11  248.673174.092   255.2 3176.18   263.3 3176.57
   279.7 3183.97   283.5 3186.55   310.4 3209.89   318.3 3215.34   326.1 3217.49
   340.7 3219.35   358.6 3222.96   365.5 3225.49   377.2 3231.83 385.138 3233.91
#Mann= 3 ,-1,0
       0      .1       0  206.99    .045       0  248.67      .1       0
Bank Sta=206.99,248.67
XS Rating Curve= 0 ,0
Exp/Cntr(USF)=0,0
Exp/Cntr=0.3,0.1
LCMann Table=0

Chan Stop Cuts=-1
Use User Specified Reach Order=0
Composite Channel Slope=5